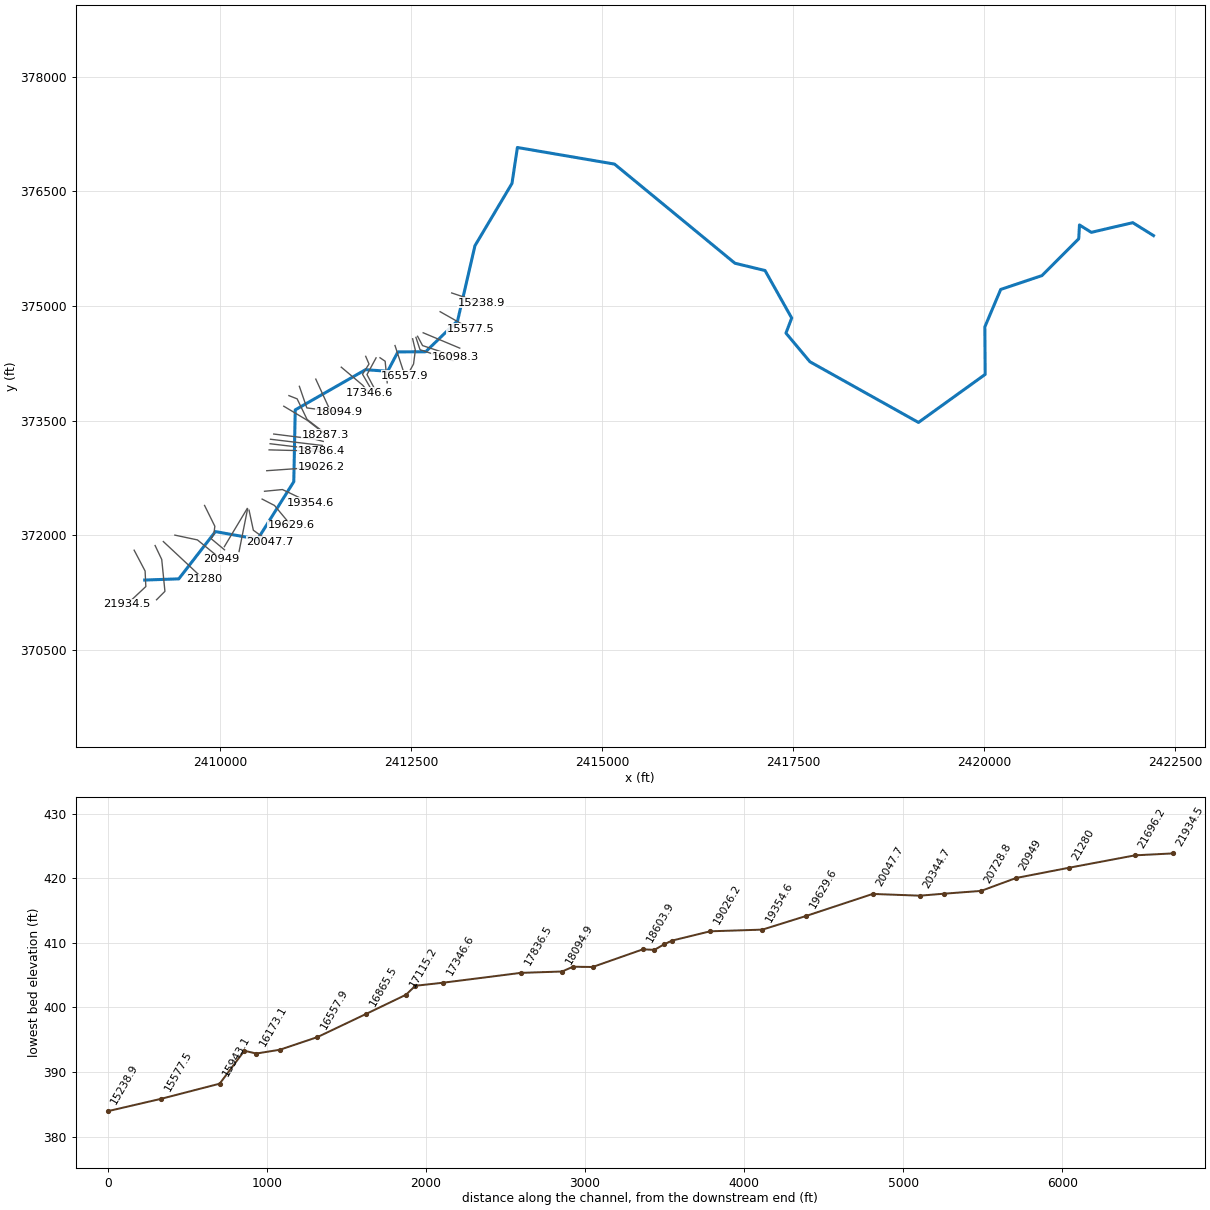
--- HOKERUN.prj (project) ---

Proj Title=HOKERUN
Current Plan=p01
Default Exp/Contr=0,0
English Units
Geom File=g01
Flow File=f01
Plan File=p01
BEGIN DESCRIPTION:
END DESCRIPTION:
DSS Export Rating Curves= 0
DSS Export Rating Curve Sorted= 0
DSS Export Volume Flow Curves= 0
DXF OffsetX= 0
DXF OffsetY= 0
DXF ScaleX= 0
DXF ScaleY= 0

--- HOKERUN.p01 (plan) ---

Plan Title=Floodplain
Program Version=4.00
Geom File=g01
Flow File=f01
K Sum by GR=0
Std Step Tol=0.01
Critical Tol=0.01
Num of Std Step Trials=20
Max Error Tol=0.3
Flow Tol Ratio=0.001
Split Flow NTrial=30
Split Flow Tol=0.02
Split Flow Ratio=0.02
Log Output Level=0
Friction Slope Method=1
Unsteady Friction Slope Method=2
Unsteady Bridges Friction Slope Method=1
Global Log Level=0
CheckData=False
Run HTab=0
Run UNet=0
Run PostProcess=0
UNET Theta=0
UNET Theta Warmup=0
UNET ZTol=0
UNET ZSATol=0
UNET MxIter=0
UNET MaxInSteps=0
UNET DtIC=0
UNET DtMin=0
UNET MaxCRTS=0
UNET WFStab=0
UNET SFStab=0
UNET WFX=0
UNET SFX=0
UNET DSS MLevel=0
UNET DZMax Abort=0
UNET Convert EG Bridges=0
UNET Use Existing IB Tables=0
UNET Froude Limit=0
UNET Froude Power=0
Write IC File=0
Echo Input=False
Echo Output=False
Write Detailed=0

--- HOKERUN.f01 (steady flow) ---

Flow Title=NFF Regression Equation
Program Version=4.00
Number of Profiles=1
Profile Names=P100yr
River Rch & RM=HOKERUN,Main      ,21934.5
653.0382
River Rch & RM=HOKERUN,Main      ,21280
617.7495
River Rch & RM=HOKERUN,Main      ,20728.8
1154.390
River Rch & RM=HOKERUN,Main      ,18786.4
1242.209
River Rch & RM=HOKERUN,Main      ,13194.9
1348.643
River Rch & RM=HOKERUN,Main      ,12658.5
1628.921
River Rch & RM=HOKERUN,Main      ,12225.1
1632.184
River Rch & RM=HOKERUN,Main      ,11860.2
1862.922
River Rch & RM=HOKERUN,Main      ,11161.5
1919.850
River Rch & RM=HOKERUN,Main      ,2798.2
2444.801
River Rch & RM=HOKERUN,Main      ,2798.2
2090.258
River Rch & RM=HOKERUN,Main      ,13
2525.965
Boundary for River Rch & Prof#=HOKERUN,Main      ,1
Up Type=0
Dn Type=3
Dn Slope=0.003631

--- HOKERUN.g01 (geometry) ---

Geom Title=USGS 10m DEM
Program Version=4.10

River Reach=HOKERUN         ,Main
Reach XY= 30
     2409014.672      371416.328     2409460.853      371431.953
      2409940.02      372050.009     2410493.839       371951.05
     2410966.061      372702.787     2410985.159      373642.023
     2411905.297      374168.064     2412195.228      374147.231
     2412328.908      374400.703     2412691.756      374402.439
     2413110.159      374806.953     2413337.589      375789.592
     2413821.964      376603.828     2413893.145      377074.314
     2415163.978        376857.3     2416740.367      375560.425
     2417134.464      375464.939     2417483.422      374843.412
     2417408.289      374646.339     2417722.525      374271.339
     2419142.664      373477.936     2420015.928      374106.409
     2420011.588      374727.936     2420219.053       375217.52
     2420759.852      375398.943     2421240.755      375880.714
     2421250.129       376060.93     2421405.077      375964.575
     2421948.045      376090.877     2422219.504      375921.867

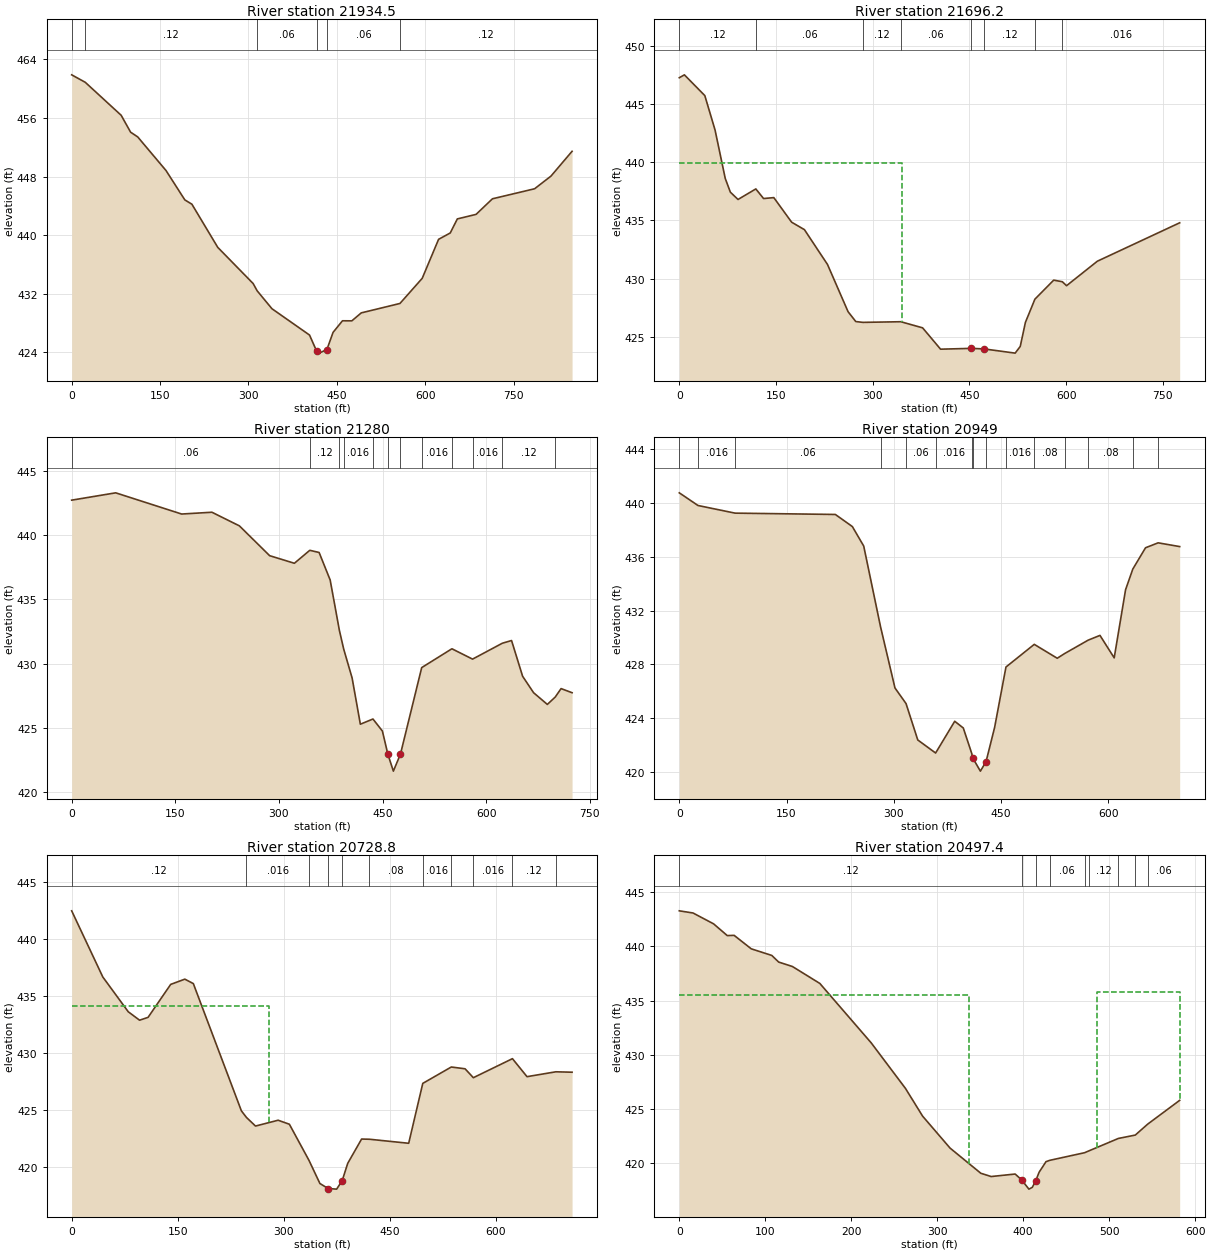
Type RM Length L Ch R = 1 ,21934.5 ,236.3,238.3,240.3
XS GIS Cut Line= 4
     2408876.664      371806.821     2409020.013      371534.298
     2409029.442      371331.127     2408782.914      371100.224
#Sta/Elev= 30
       0   461.9   23.03460.8785      84  456.37     100  454.06     112  453.42
     160  448.83     192  444.81     204  444.22   247.9  438.32   307.9  433.38
  314.72432.3875   339.8  429.94   403.6  426.34   415.6  424.16   419.6  423.87
     433  424.34   443.5   426.7   459.5  428.29   475.4  428.28   491.4  429.37
  557.03430.6557   594.8  434.09   622.6  439.42   642.4  440.29   654.4  442.21
   686.2  442.83     714  444.96   785.5  446.33   813.3  448.06   849.1  451.45
#Mann= 6 ,-1 , 0
       0    .016       0   23.03     .12       0  314.72     .06       0
   415.6    .045       0     433     .06       0  557.03     .12       0
Bank Sta=415.6,433
XS Rating Curve= 0 ,0
Exp/Cntr=0.3,0.1

Type RM Length L Ch R = 1 ,21696.2 ,387.1,416.2,445.3
XS GIS Cut Line= 4
      2409150.97      371867.585     2409237.708      371685.113
     2409279.442      371268.627     2409169.626      371158.377
#Sta/Elev= 30
       0   447.3     7.9  447.55    39.6  445.76    55.5  442.79    71.3  438.62
    79.2  437.44    91.1  436.81  118.73437.7188   130.7  436.89   146.6  436.97
   174.3  434.85   194.1  434.21   229.9  431.21   261.8  427.14   273.8  426.29
  284.76  426.22  343.61426.2753   377.4  425.75   405.3  423.91   453.2  423.98
   473.1  423.93     521  423.57   528.9  424.15   536.9  426.22  551.61428.2183
   580.8  429.86  594.21429.7205   600.7  429.38   648.5  431.49   776.2   434.8
#Mann= 8 ,-1 , 0
       0     .12       0  118.73     .06       0  284.76     .12       0
  343.61     .06       0   453.2    .045       0   473.1     .12       0
  551.61     .06       0  594.21    .016       0
#XS Ineff= 2 , 0
          346.03  439.94
Permanent Ineff=
       F       F
Bank Sta=453.2,473.1
XS Rating Curve= 0 ,0
Exp/Cntr=0.3,0.1

Type RM Length L Ch R = 1 ,21280   ,328.5,331,333.6
XS GIS Cut Line= 2
     2409258.609      371919.669     2409788.116      371425.304
#Sta/Elev= 30
       0  442.72    63.7  443.29   159.2  441.64     203  441.78   242.8  440.72
   286.6   438.4   322.4  437.81   344.7 438.818   358.2  438.65   374.2  436.51
  387.61432.5725  393.87431.1187     406  428.88   417.9  425.29  436.16425.6941
   449.8  424.76   457.7  422.96   465.7  421.64     476  422.97  506.71429.6935
  550.46431.1587  580.35430.3531  623.45431.5901   636.8   431.8   652.8  429.02
   668.7  427.74   688.6  426.83  699.99427.4008   708.5  428.06   724.4  427.74
#Mann= 12 ,-1 , 0
       0     .06       0   344.7     .12       0  387.61     .06       0
  393.87    .016       0  436.16     .12       0   457.7    .045       0
     476     .08       0  506.71    .016       0  550.46     .08       0
  580.35    .016       0  623.45     .12       0  699.99     .06       0
Bank Sta=457.7,476
XS Rating Curve= 0 ,0
Exp/Cntr=0.3,0.1

Type RM Length L Ch R = 1 ,20949   ,260.8,220.2,126.1
XS GIS Cut Line= 3
      2409409.65       372003.87     2409704.789       371941.37
      2410013.81      371690.061
#Sta/Elev= 30
       0  440.77   26.17439.8271   78.01439.2586   218.3  439.16   242.1  438.26
     258  436.81  281.48430.8163   301.7  426.25  317.21425.0858   333.6  422.38
  358.57421.4076   385.3  423.77   397.3  423.27  409.21421.3578   410.8  421.01
   421.2  420.06   429.1  420.76   441.1  423.31  456.98427.8058  496.58429.4936
   528.7  428.46  539.13428.8111  571.96429.8065   588.5  430.16   608.4  428.49
   624.3  433.56  634.44435.0973   652.2  436.68  669.88 437.049     700  436.77
#Mann= 15 ,-1 , 0
       0     .08       0   26.17    .016       0   78.01     .06       0
  281.48     .12       0  317.21     .06       0  358.57    .016       0
  409.21     .08       0   410.8    .045       0   429.1     .08       0
  456.98    .016       0  496.58     .08       0  539.13    .016       0
  571.96     .08       0  634.44     .12       0  669.88     .06       0
Bank Sta=410.8,429.1
XS Rating Curve= 0 ,0
Exp/Cntr=0.3,0.1

Type RM Length L Ch R = 1 ,20728.8 ,246.1,231.4,270.1
XS GIS Cut Line= 5
     2409798.142      372392.275     2409932.821      372119.835
     2409919.626      372014.627     2409882.126      371959.592
     2410059.383      371811.589
#Sta/Elev= 30
       0  442.46      44  436.66      80  433.61      96  432.87     108  433.12
     140  436.01     160  436.47     172  436.08   239.9  424.93  247.08424.3474
   259.9  423.59   291.9   424.1   307.8  423.75   335.5420.5844     351  418.55
   362.8  418.11   374.6  418.06   382.4  418.79   390.3  420.32   409.9  422.45
  420.98422.4337   476.5  422.08  496.42427.3315  536.74428.7668   556.2  428.61
  567.92427.8299  623.19429.4975   643.8  427.92  684.55428.3465   707.5  428.31
#Mann= 11 ,-1 , 0
       0     .12       0  247.08    .016       0   335.5     .12       0
   362.8    .045       0   382.4     .12       0  420.98     .08       0
  496.42    .016       0  536.74     .08       0  567.92    .016       0
  623.19     .12       0  684.55     .06       0
#XS Ineff= 2 , 0
          279.45  434.09
Permanent Ineff=
       F       F
Bank Sta=362.8,382.4
XS Rating Curve= 0 ,0
Exp/Cntr=0.3,0.1

Type RM Length L Ch R = 1 ,20497.4 ,139.1,152.7,165.8
XS GIS Cut Line= 2
     2410356.692      372351.953     2410057.213      371852.821
#Sta/Elev= 30
       0  443.27      16  443.07    39.9  442.07    55.8  440.99    63.8  441.01
    83.7  439.77   107.6  439.16   115.6  438.55   131.6  438.14   163.5  436.58
   223.3   431.1   263.1  426.91   283.1  424.35     315  421.41   350.8  419.09
   362.8  418.79   390.7  419.02   398.2  418.49   406.7  417.63   410.6  417.79
   414.6  418.39   418.6  419.19   426.6  420.16     431 420.284  471.46420.9845
  476.71421.1609  510.79422.2998  530.46422.6101  544.87423.6169   582.1  425.81
#Mann= 9 ,-1 , 0
       0     .12       0   398.2    .045       0   414.6     .12       0
     431     .06       0  471.46     .08       0  476.71     .12       0
  510.79     .06       0  530.46     .12       0  544.87     .06       0
#XS Ineff= 2 , 0
          337.45  435.51  485.75          435.82
Permanent Ineff=
       F       F
Bank Sta=398.2,414.6
XS Rating Curve= 0 ,0
Exp/Cntr=0.3,0.1

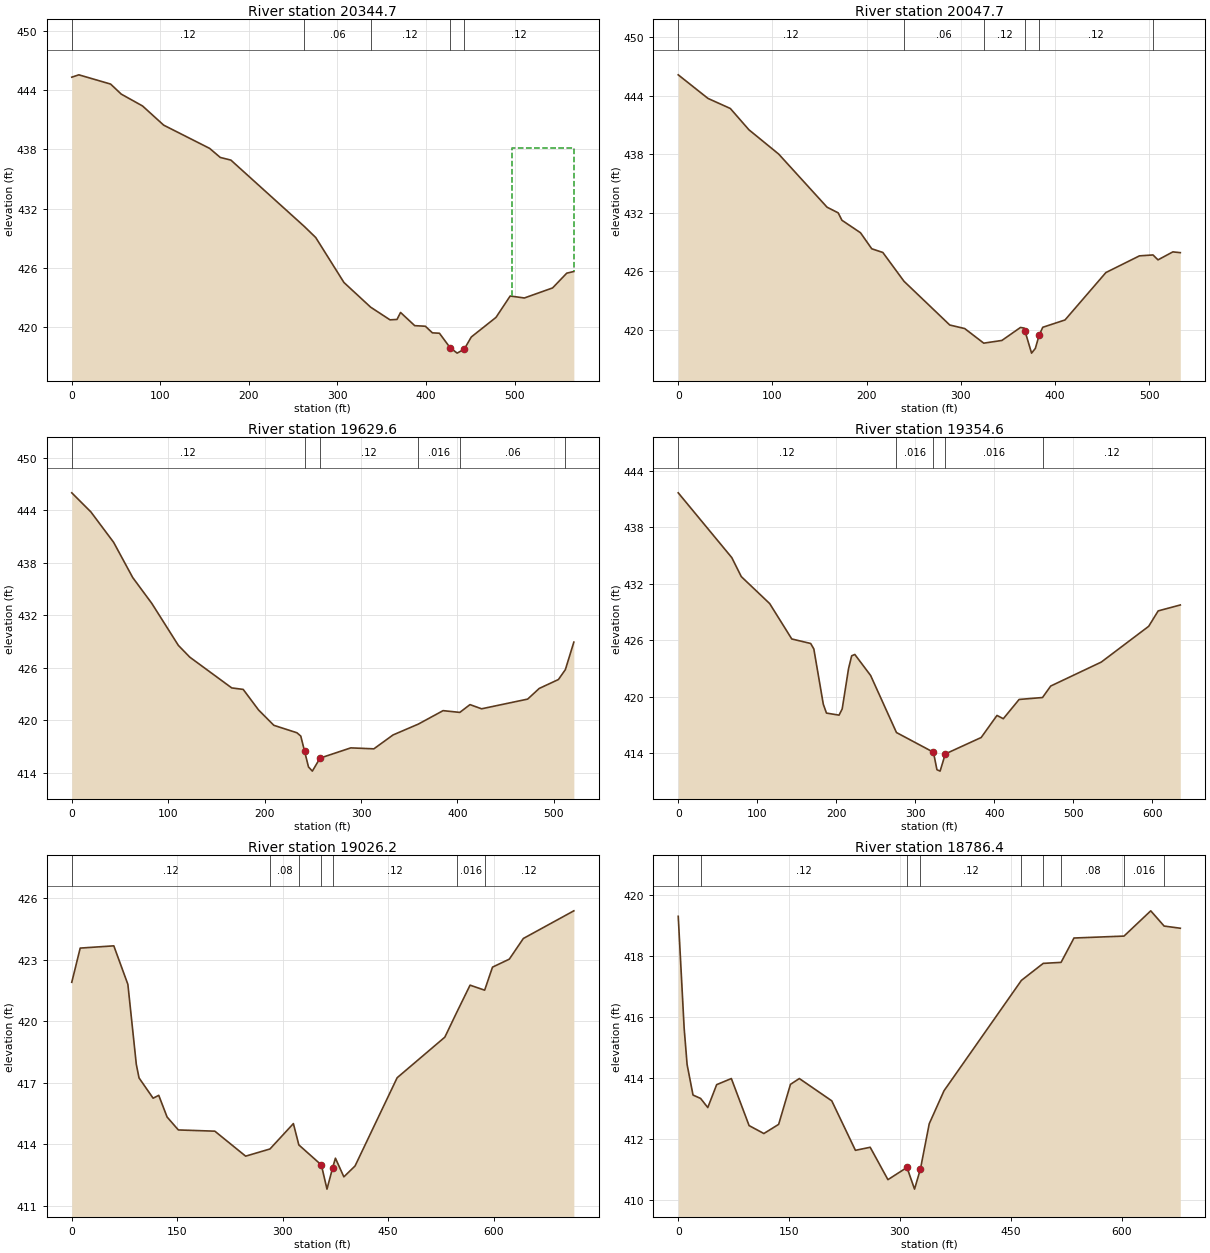
Type RM Length L Ch R = 1 ,20344.7 ,253.9,297,340.3
XS GIS Cut Line= 2
     2410361.032      372345.443     2410249.928       371789.46
#Sta/Elev= 30
       0  445.34       8  445.58    43.9  444.64    55.9  443.62    79.9  442.42
   103.8  440.47   155.7  438.11   167.7  437.19   179.7  436.92  262.59430.1851
   275.5  429.06   307.4  424.49   337.5421.9883   359.4   420.7   367.3  420.74
   371.3  421.45   387.3  420.11   399.3  420.05   407.3  419.38   415.2  419.34
   427.2  417.88   435.2  417.32   443.2  417.72   451.2  418.96   479.1  420.95
   495.1  423.12   511.1  422.92     543  423.94     559  425.44     567  425.61
#Mann= 5 ,-1 , 0
       0     .12       0  262.59     .06       0   337.5     .12       0
   427.2    .045       0   443.2     .12       0
#XS Ineff= 2 , 0
                           497.1          438.17
Permanent Ineff=
       F       F
Bank Sta=427.2,443.2
XS Rating Curve= 0 ,0
Exp/Cntr=0.3,0.1

Type RM Length L Ch R = 1 ,20047.7 ,427.6,418,408.4
XS GIS Cut Line= 3
     2410380.564      372330.252     2410436.987      372067.665
     2410651.831      371913.585
#Sta/Elev= 30
       0  446.12    31.6   443.7    55.3  442.67      75  440.49   106.6     438
     158  432.55   169.8  431.97   173.8  431.21   193.5  429.93   205.4  428.29
   217.2  427.91  239.69424.9537   288.3  420.47   304.1  420.11  324.33418.6121
   343.6  418.89   363.3  420.22   367.2  420.16   368.2  419.82   375.1  417.59
   379.1  418.07   383.2  419.44     387  420.24   410.6  420.99     454  425.85
   489.6  427.56  504.03427.6554   509.3  427.15   525.1  427.97     533  427.89
#Mann= 6 ,-1 , 0
       0     .12       0  239.69     .06       0  324.33     .12       0
   368.2    .045       0   383.2     .12       0  504.03    .016       0
Bank Sta=368.2,383.2
XS Rating Curve= 0 ,0
Exp/Cntr=0.3,0.1

Type RM Length L Ch R = 1 ,19629.6 ,257.6,275.1,292.5
XS GIS Cut Line= 3
     2410552.011      372475.224      2410713.47      372391.891
     2410930.484      372131.474
#Sta/Elev= 30
       0  446.02    19.8  443.84    43.4  440.36    63.2  436.33      83  433.37
   110.6  428.56   122.4  427.22   165.9   423.7   177.8  423.53   193.7  421.18
   209.6  419.42   233.5  418.57   237.5  418.19   241.5  416.43   245.5  414.66
   249.5  414.18   257.5  415.67   289.4  416.84   313.3  416.73   333.2  418.32
  359.47419.5629   385.1   421.1  402.43420.8993     413  421.79     425  421.31
   472.8  422.42   484.8  423.64   504.7  424.66   511.9  425.79   520.7  428.94
#Mann= 6 ,-1 , 0
       0     .12       0   241.5    .045       0   257.5     .12       0
  359.47    .016       0  402.43     .06       0   511.9     .12       0
Bank Sta=241.5,257.5
XS Rating Curve= 0 ,0
Exp/Cntr=0.3,0.1

Type RM Length L Ch R = 1 ,19354.6 ,308.9,328.3,347.6
XS GIS Cut Line= 3
     2410583.261      372577.655     2410817.636      372600.224
     2411178.748      372428.349
#Sta/Elev= 30
       0  441.69    67.8  434.79    79.8  432.77   115.7   429.9   143.7  426.13
   167.6  425.65   171.6  425.07   183.6  419.18   187.6  418.24   203.5  418.02
   207.5  418.68   215.5  422.96   219.5  424.34   223.5  424.48   243.5  422.24
  276.18 416.169     323  414.07   327.4  412.21   331.4  412.06     338  413.89
   383.4  415.64   403.4  417.99   411.4  417.64   431.4  419.69     461 419.896
   471.4  421.12   535.4  423.67   595.4  427.48   607.4  429.12   635.4  429.75
#Mann= 5 ,-1 , 0
       0     .12       0  276.18    .016       0     323    .045       0
     338    .016       0     461     .12       0
Bank Sta=323,338
XS Rating Curve= 0 ,0
Exp/Cntr=0.3,0.1

Type RM Length L Ch R = 1 ,19026.2 ,243.4,239.8,236.2
XS GIS Cut Line= 2
     2410612.252      372846.471     2411324.574      372896.658
#Sta/Elev= 30
       0   421.9      12  423.57    59.8  423.68    79.8   421.8    91.8  417.89
    95.7  417.23   115.7  416.24   123.7  416.38   135.6  415.32   151.6  414.69
   203.5  414.63   247.3  413.41  281.91413.7607   315.2     415  322.96 413.959
     355  412.98     363   411.8     371  412.84     375  413.31     387   412.4
   402.9  412.93   462.8  417.24   530.6  419.22   547.2 420.408   566.5  421.76
  587.25421.5152   598.4  422.64   622.3  423.03   642.3  424.04   714.1  425.39
#Mann= 7 ,-1 , 0
       0     .12       0  281.91     .08       0  322.96     .12       0
     355    .045       0     371     .12       0   547.2    .016       0
  587.25     .12       0
Bank Sta=355,371
XS Rating Curve= 0 ,0
Exp/Cntr=0.3,0.1

Type RM Length L Ch R = 1 ,18786.4 ,55.4,51.8,48.3
XS GIS Cut Line= 2
      2410643.15      373119.097     2411322.404      373101.736
#Sta/Elev= 30
       0  419.29       8  415.63      12  414.44      20  413.44   30.29413.3284
      40  413.03      52  413.78    71.9  413.98    95.9  412.44   115.9  412.18
   135.9  412.48   151.9  413.79   163.9  413.98   207.8  413.25   239.8  411.63
   259.8  411.73   283.8  410.67   309.6  411.07   319.8  410.36   327.8  411.02
   339.7   412.5   359.7  413.58  464.46417.1937  493.98417.7498  518.12417.7826
   535.6  418.58  603.32418.6432   639.5  419.47   657.6418.9713   679.5   418.9
#Mann= 9 ,-1 , 0
       0     .08       0   30.29     .12       0   309.6    .045       0
   327.8     .12       0  464.46     .08       0  493.98    .016       0
  518.12     .08       0  603.32    .016       0   657.6     .12       0
Bank Sta=309.6,327.8
XS Rating Curve= 0 ,0
Exp/Cntr=0.3,0.1

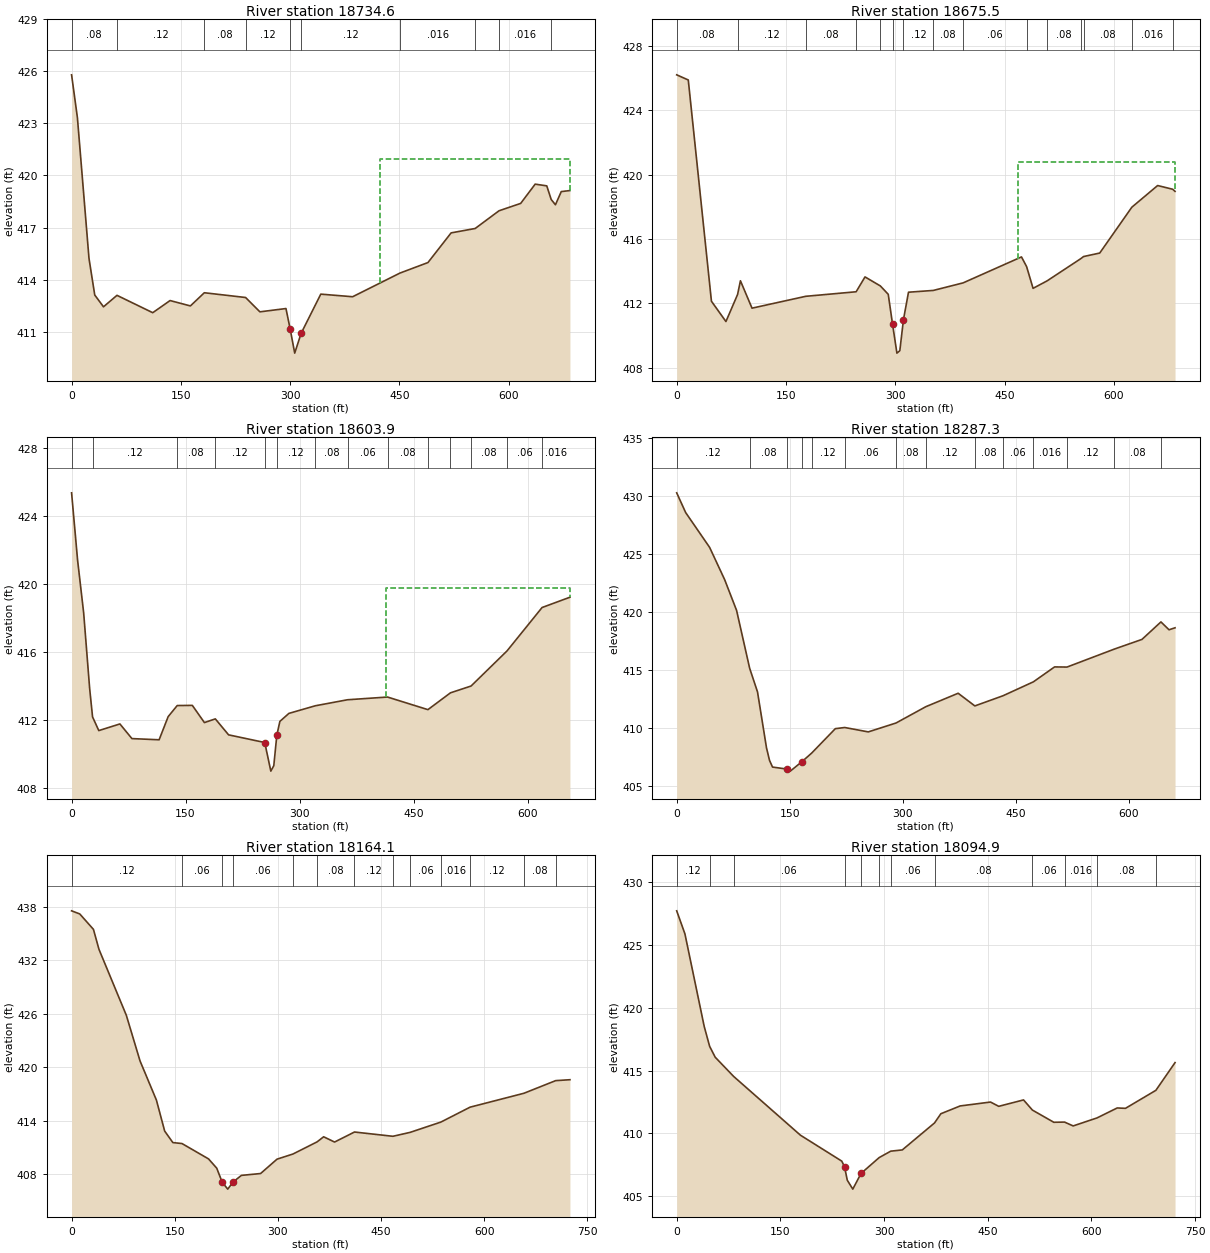
Type RM Length L Ch R = 1 ,18734.6 ,59.1,59.1,59.1
XS GIS Cut Line= 2
     2410656.171      373199.393     2411335.425      373118.012
#Sta/Elev= 30
       0   425.8       8  423.33    23.9  415.22    31.8  413.11    43.8  412.43
   62.33413.0907   111.4  412.09   135.2  412.79   163.1  412.48  182.22  413.24
  238.87412.9665   258.5  412.14   294.3  412.33   300.1  411.14   306.3  409.76
   315.1   410.9   342.1  413.16   385.8  413.01  450.61414.3712   489.2  414.98
     521  416.69  554.03416.9435  586.74417.9641   616.5  418.39   636.4   419.5
   652.3   419.4  658.37418.6172   664.2  418.31   672.2  419.07   684.1  419.13
#Mann= 10 ,-1 , 0
       0     .08       0   62.33     .12       0  182.22     .08       0
  238.87     .12       0   300.1    .045       0   315.1     .12       0
  450.61    .016       0  554.03     .08       0  586.74    .016       0
  658.37     .12       0
#XS Ineff= 2 , 0
                          423.71          420.93
Permanent Ineff=
       F       F
Bank Sta=300.1,315.1
XS Rating Curve= 0 ,0
Exp/Cntr=0.3,0.1

Type RM Length L Ch R = 1 ,18675.5 ,71.9,71.7,71.4
XS GIS Cut Line= 2
     2410661.597      373257.986      2411340.85      373176.606
#Sta/Elev= 30
       0  426.19    15.9  425.87    47.7  412.14    67.6  410.88   83.58412.5574
    87.5  413.41   103.4  411.71   177.1412.4457  246.35412.7281   258.5  413.65
  279.55413.0899   290.4  412.57   296.3  410.72   302.3  408.92   306.3  409.07
   311.3     411   318.2   412.7  352.33412.8108  393.18413.2791   473.3  414.89
  480.35414.2881   489.2  412.94   508.4413.4023   554.5414.7756  558.55414.9138
   580.7  415.13   624.8 417.975   660.2  419.32  680.86419.0896   684.1  418.96
#Mann= 15 ,-1 , 0
       0     .08       0   83.58     .12       0   177.1     .08       0
  246.35    .016       0  279.55     .12       0   296.3    .045       0
   311.3     .12       0  352.33     .08       0  393.18     .06       0
  480.35    .016       0   508.4     .08       0   554.5     .12       0
  558.55     .08       0   624.8    .016       0  680.86     .12       0
#XS Ineff= 2 , 0
                          467.84          420.76
Permanent Ineff=
       F       F
Bank Sta=296.3,311.3
XS Rating Curve= 0 ,0
Exp/Cntr=0.3,0.1

Type RM Length L Ch R = 1 ,18603.9 ,332.4,316.5,299.3
XS GIS Cut Line= 3
     2410703.914      373326.346     2411239.939      373259.071
     2411351.701      373229.775
#Sta/Elev= 30
       0  425.35     7.9   421.4    15.9   418.3    23.8  413.85   27.61412.1926
    35.8  411.39    63.6  411.78    79.4  410.92   115.2  410.85   127.1  412.21
     139  412.86   158.9  412.87   174.8  411.86  189.16412.0777   206.6  411.14
   254.2  410.69   262.2  409.01   266.1  409.33   270.1  411.12   274.1  411.93
     286   412.4  320.78412.8474  363.11   413.2  415.76  413.36  468.91  412.62
  498.59 413.607  525.72414.0074  572.96416.0652  619.14418.6158   655.8  419.22
#Mann= 14 ,-1 , 0
       0     .08       0   27.61     .12       0     139     .08       0
  189.16     .12       0   254.2    .045       0   270.1     .12       0
  320.78     .08       0  363.11     .06       0  415.76     .08       0
  468.91    .016       0  498.59     .12       0  525.72     .08       0
  572.96     .06       0  619.14    .016       0
#XS Ineff= 2 , 0
                          413.11          419.76
Permanent Ineff=
       F       F
Bank Sta=254.2,270.1
XS Rating Curve= 0 ,0
Exp/Cntr=0.3,0.1

Type RM Length L Ch R = 1 ,18287.3 ,145,123.2,102.7
XS GIS Cut Line= 3
     2410835.208      373689.844     2411142.282      373506.467
     2411382.083      373319.835
#Sta/Elev= 30
       0  430.25    11.9  428.55    43.7  425.55    63.6  422.78    79.5  420.12
   96.85415.1329   107.3  413.09   119.2  408.28   123.2   407.2   127.2  406.62
     147  406.44   150.8  406.27   165.8  407.06   179.1407.8198   210.6  409.93
  223.04 410.029   254.3  409.65  291.12410.4159  330.68411.8208   373.6  412.98
  395.76411.8878  433.19412.7657  473.52 413.965   501.6  415.25  518.11415.2364
  580.82416.7832   617.6  417.62  642.78419.1268   653.5  418.45   661.5  418.62
#Mann= 14 ,-1 , 0
       0     .12       0   96.85     .08       0     147    .045       0
   165.8     .08       0   179.1     .12       0  223.04     .06       0
  291.12     .08       0  330.68     .12       0  395.76     .08       0
  433.19     .06       0  473.52    .016       0  518.11     .12       0
  580.82     .08       0  642.78    .016       0
Bank Sta=147,165.8
XS Rating Curve= 0 ,0
Exp/Cntr=0.3,0.1

Type RM Length L Ch R = 1 ,18164.1 ,73.5,69.2,64.7
XS GIS Cut Line= 4
     2410902.482      373828.733     2411009.904      373786.415
     2411140.112      373517.318     2411386.423      373328.516
#Sta/Elev= 30
       0  437.52    11.9  437.17    31.8  435.44    39.8  433.21    79.6  425.81
    99.5   420.7   123.4  416.29   135.4  412.82   147.3  411.53  160.54411.4224
   199.2   409.7   211.1  408.66   219.1  407.08   227.1  406.31     235  407.12
     247  407.85   274.9  408.06   298.8  409.67  321.99410.2476  357.08411.6088
   366.6  412.18   382.5  411.59  411.45412.7141  467.32412.2356  492.43412.6765
  537.15413.8303  579.52415.4999  657.95417.0612  704.02 418.476   724.8  418.58
#Mann= 13 ,-1 , 0
       0     .12       0  160.54     .06       0   219.1    .045       0
     235     .06       0  321.99     .12       0  357.08     .08       0
  411.45     .12       0  467.32     .08       0  492.43     .06       0
  537.15    .016       0  579.52     .12       0  657.95     .08       0
  704.02    .016       0
Bank Sta=219.1,235
XS Rating Curve= 0 ,0
Exp/Cntr=0.3,0.1

Type RM Length L Ch R = 1 ,18094.9 ,254.8,258.4,262.1
XS GIS Cut Line= 3
     2411039.201      373950.261     2411136.857      373668.143
     2411555.694      373612.804
#Sta/Elev= 30
       0  427.72    11.9  425.89    39.8  418.52   47.66416.9352    55.7  416.07
   82.35414.5419   179.1  409.86   238.8   407.8   242.8  407.36   246.8  406.28
   254.8  405.57   266.7  406.82  292.98408.0811  309.67408.5913   326.4  408.69
  373.03410.8376   382.2  411.57   410.1  412.19     454   412.5   465.9  412.16
   501.8  412.67  514.64411.8617   545.6  410.89  561.18410.9058   573.6   410.6
  608.22411.2393   637.3  412.03   649.3     412  693.27413.4328     721  415.64
#Mann= 12 ,-1 , 0
       0     .12       0   47.66     .08       0   82.35     .06       0
   242.8    .045       0   266.7     .06       0  292.98    .016       0
  309.67     .06       0  373.03     .08       0  514.64     .06       0
  561.18    .016       0  608.22     .08       0  693.27    .016       0
Bank Sta=242.8,266.7
XS Rating Curve= 0 ,0
Exp/Cntr=0.3,0.1

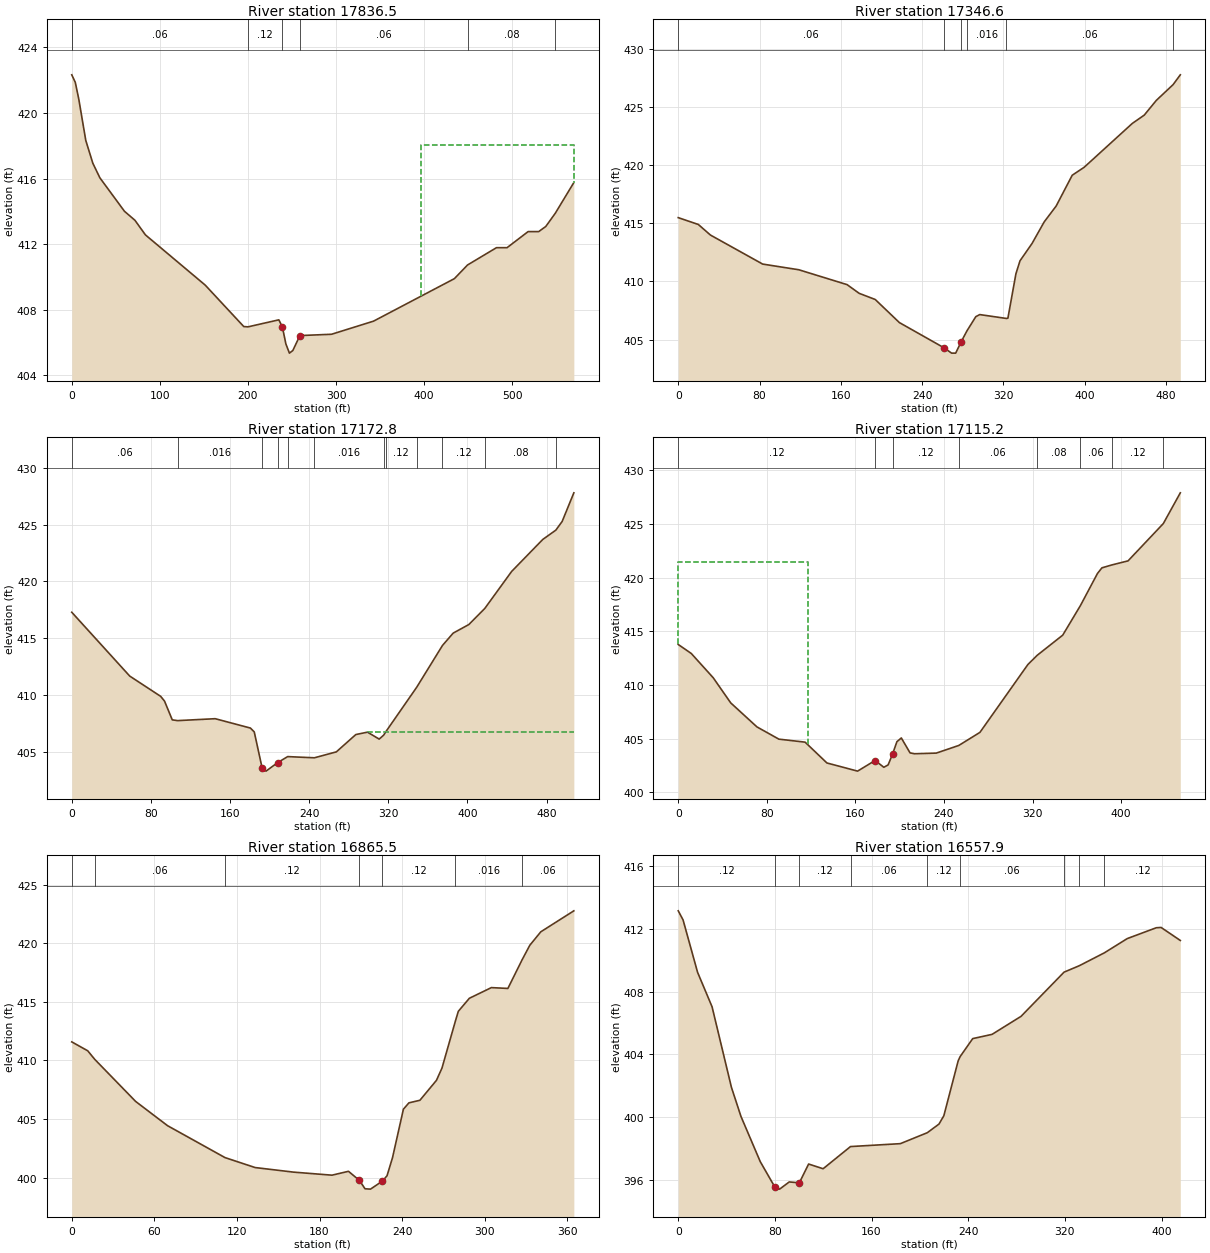
Type RM Length L Ch R = 1 ,17836.5 ,473.1,489.9,506.5
XS GIS Cut Line= 3
     2411254.044      374044.662     2411441.762       373635.59
     2411560.034      373617.144
#Sta/Elev= 30
       0  422.33     .74422.2449       4  421.87       8  420.84    15.9  418.33
    23.9  416.94    31.9  416.05    59.8  414.01    71.7  413.46    83.6  412.57
   151.4  409.51   195.2  406.98  199.98 406.962     235  407.39     239  406.96
     243  405.92     247  405.36   250.9  405.52   258.9  406.43   294.8  406.51
   342.5  407.31   434.2   409.9  449.17410.7354     482  411.79     494  411.79
   517.9  412.77   529.9  412.77   537.9  413.08  548.72413.8871   569.8  415.76
#Mann= 7 ,-1 , 0
       0     .12       0     .74     .06       0  199.98     .12       0
     239    .045       0   258.9     .06       0  449.17     .08       0
  548.72    .016       0
#XS Ineff= 2 , 0
                          396.47          418.08
Permanent Ineff=
       F       F
Bank Sta=239,258.9
XS Rating Curve= 0 ,0
Exp/Cntr=0.3,0.1

Type RM Length L Ch R = 1 ,17346.6 ,236.6,173.8,100.5
XS GIS Cut Line= 3
     2411587.682      374200.825     2411866.327       373966.45
      2411951.31      373867.926
#Sta/Elev= 30
       0   415.5    19.8  414.91    31.7     414    83.1   411.5   118.7  411.01
   166.2  409.73   178.1  408.98   193.9  408.45   217.7  406.46   261.2  404.31
   269.1  403.83   273.1  403.83   278.5  404.81  284.13405.7382   292.9  406.97
   296.8  407.15     323406.8169   324.5  406.84   332.4  410.67   336.4  411.78
   348.3  413.28   360.2  415.13     372   416.5   387.8  419.15   399.6  419.84
   446.9  423.61   458.7  424.33   470.6   425.6  487.11 426.957   494.2   427.8
#Mann= 6 ,-1 , 0
       0     .06       0   261.2    .045       0   278.5     .06       0
  284.13    .016       0     323     .06       0  487.11    .016       0
Bank Sta=261.2,278.5
XS Rating Curve= 0 ,0
Exp/Cntr=0.3,0.1

Type RM Length L Ch R = 1 ,17172.8 ,86,57.6,76
XS GIS Cut Line= 4
     2411907.473      374342.665     2411950.702      374242.144
     2411865.807      374108.811     2411986.032      373900.912
#Sta/Elev= 30
       0   417.3    58.6   411.7    89.9  409.92    93.8   409.5   101.6  407.86
  106.98407.7921     145  407.96   180.6  407.14   184.5   406.8   192.4  403.66
   196.4  403.36   208.2  404.11  218.27404.6342   245.3  404.53   267.5  405.05
   287.2  406.57     299  406.78   310.8  406.17  315.32406.5153  317.48406.8123
  348.71410.7165  374.79414.3869   385.6  415.47   401.4  416.22  417.57417.6339
   444.7  420.88   476.2  423.69  489.42424.5084   495.8  425.27   507.6  427.78
#Mann= 12 ,-1 , 0
       0     .06       0  106.98    .016       0   192.4    .045       0
   208.2    .016       0  218.27     .08       0   245.3    .016       0
  315.32     .06       0  317.48     .12       0  348.71     .06       0
  374.79     .12       0  417.57     .08       0  489.42    .016       0
#XS Ineff= 2 , 0
                          298.87          406.81
Permanent Ineff=
       F       F
Bank Sta=192.4,208.2
XS Rating Curve= 0 ,0
Exp/Cntr=0.3,0.1

Type RM Length L Ch R = 1 ,17115.2 ,189.9,249.6,272.3
XS GIS Cut Line= 3
     2412043.324      374322.787     2411924.574      374104.037
     2412020.755      373923.481
#Sta/Elev= 30
       0  413.78    11.8  412.94    31.6  410.68    47.4  408.34    71.1   406.1
    90.9  404.96   114.6  404.68   134.3  402.74     162  401.98   177.8  402.97
   185.7  402.34   189.6  402.56   193.6  403.57   197.5  404.72   201.5  405.07
   209.4  403.68   213.4   403.6   233.1  403.66  253.39404.3706   272.5  405.59
   315.8  411.91  324.17 412.767   347.3  414.65  363.27417.4033   378.7   420.4
   382.7  420.92  391.66421.1916   406.3  421.57  438.15425.0445   453.5  427.91
#Mann= 8 ,-1 , 0
       0     .12       0   177.8    .045       0   193.6     .12       0
  253.39     .06       0  324.17     .08       0  363.27     .06       0
  391.66     .12       0  438.15    .016       0
#XS Ineff= 2 , 0
          117.28  421.43
Permanent Ineff=
       F       F
Bank Sta=177.8,193.6
XS Rating Curve= 0 ,0
Exp/Cntr=0.3,0.1

Type RM Length L Ch R = 1 ,16865.5 ,298.6,307.6,311.2
XS GIS Cut Line= 3
     2412094.756      374324.089     2412162.031      374278.516
     2412189.157      373996.398
#Sta/Elev= 30
       0  411.58    11.6  410.82   16.65410.0955    46.4   406.5    69.6  404.43
  111.28401.7116   133.2  400.86   161.1  400.47     189  400.21     201  400.54
     209  399.76     213  399.05     217  399.02   225.7  399.71     229  400.16
     233  401.71   240.9  405.84   244.9  406.38   252.9   406.6   264.9   408.3
   268.9  409.34  278.73413.3832   280.8  414.19   288.8   415.3   304.8  416.21
   316.8  416.14  327.09418.5768   332.7  419.82   340.7  420.97   364.7  422.76
#Mann= 7 ,-1 , 0
       0     .12       0   16.65     .06       0  111.28     .12       0
     209    .045       0   225.7     .12       0  278.73    .016       0
  327.09     .06       0
Bank Sta=209,225.7
XS Rating Curve= 0 ,0
Exp/Cntr=0.3,0.1

Type RM Length L Ch R = 1 ,16557.9 ,253.6,236.2,224.1
XS GIS Cut Line= 2
     2412291.154      374483.594     2412420.277      374088.629
#Sta/Elev= 30
       0  413.16       4  412.58      16  409.24      28  407.04      44  401.91
    51.9  400.05    67.9  397.16    79.9  395.55    83.9  395.41    91.9  395.87
   100.2  395.81   107.9  397.01   119.9  396.71  142.57398.1246   183.8  398.31
  206.14399.0094   215.8  399.56   219.8  400.09   231.7   403.6  233.29403.8624
   243.7  405.01   259.7  405.28   283.7  406.43   319.3409.2497  331.99409.6617
  352.72410.4836   371.6  411.39   395.6  412.08   399.6   412.1   415.5  411.27
#Mann= 9 ,-1 , 0
       0     .12       0    79.9    .045       0   100.2     .12       0
  142.57     .06       0  206.14     .12       0  233.29     .06       0
   319.3     .08       0  331.99     .06       0  352.72     .12       0
Bank Sta=79.9,100.2
XS Rating Curve= 0 ,0
Exp/Cntr=0.3,0.1

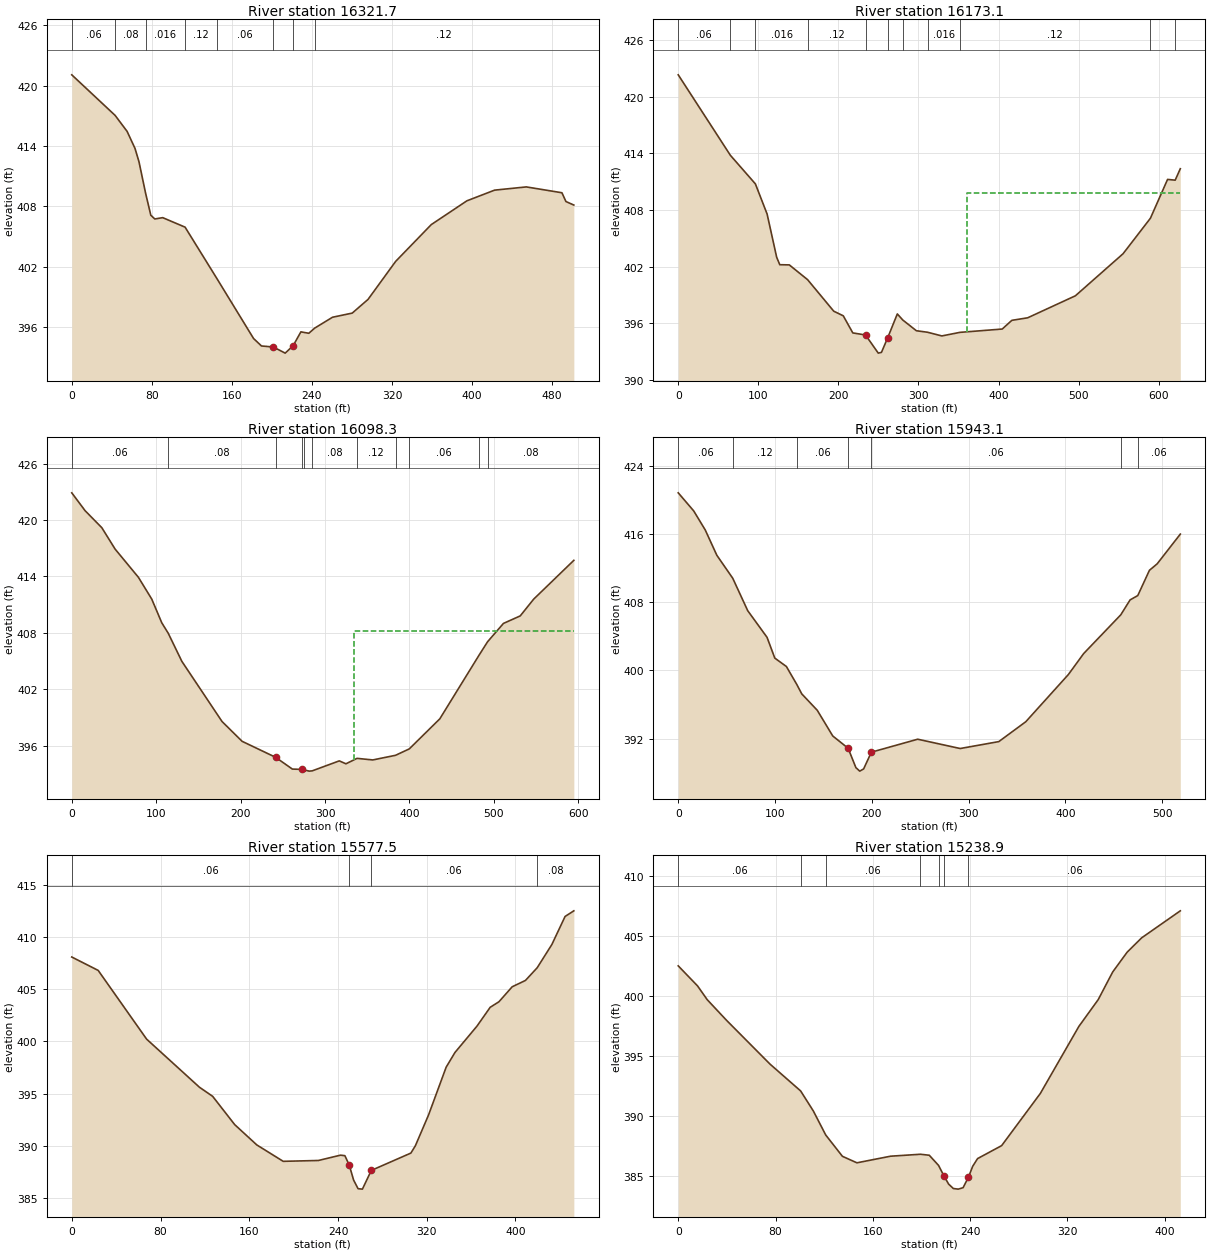
Type RM Length L Ch R = 1 ,16321.7 ,85.7,148.6,203.7
XS GIS Cut Line= 4
      2412521.84      374572.049     2412557.256      374422.049
     2412533.645      374242.188     2412453.784      374096.354
#Sta/Elev= 30
       0  421.06   43.34417.0344    55.3  415.45    63.2  413.76    67.2  412.43
   73.79 409.315      79  407.13      83  406.76    90.9  406.89  113.25405.9477
   145.4400.7923   181.7   394.9   189.6  394.16   201.4  394.06   213.3  393.45
   221.2  394.18     229  395.56   236.9  395.42  242.85 395.935   260.6  397.01
   280.3  397.42   296.1  398.78   323.7  402.55   359.3   406.2   394.9  408.56
   422.6  409.62   454.3  409.94   489.9  409.36   493.9  408.49   501.8  408.14
#Mann= 8 ,-1 , 0
       0     .06       0   43.34     .08       0   73.79    .016       0
  113.25     .12       0   145.4     .06       0   201.4    .045       0
   221.2     .06       0  242.85     .12       0
Bank Sta=201.4,221.2
XS Rating Curve= 0 ,0
Exp/Cntr=0.3,0.1

Type RM Length L Ch R = 1 ,16173.1 ,82.5,74.8,74.8
XS GIS Cut Line= 3
     2412564.895      374590.799     2412618.367      374428.993
     2413051.701      374285.243
#Sta/Elev= 30
       0  422.32   65.11 413.802   96.37410.7732     111  407.58   122.9  403.02
   126.8  402.22   138.7   402.2  161.58400.6336   194.2   397.3   206.1  396.81
     218     395   233.9  394.78   249.8  392.86   253.8  392.94   261.7  394.51
   273.6  397.01   280.4 396.367   297.4  395.23  311.33395.0708   329.2  394.68
  351.72395.0565   404.6  395.41   416.6  396.33   436.4   396.6     496  398.93
   555.5  403.38  589.67407.1378   611.1  411.25   620.6 411.168     627  412.38
#Mann= 11 ,-1 , 0
       0     .06       0   65.11     .08       0   96.37    .016       0
  161.58     .12       0   233.9    .045       0   261.7     .12       0
   280.4     .08       0  311.33    .016       0  351.72     .12       0
  589.67     .08       0   620.6     .06       0
#XS Ineff= 2 , 0
                          360.15          409.78
Permanent Ineff=
       F       F
Bank Sta=233.9,261.7
XS Rating Curve= 0 ,0
Exp/Cntr=0.3,0.1

Type RM Length L Ch R = 1 ,16098.3 ,161,155.2,149.3
XS GIS Cut Line= 3
     2412586.423      374605.035     2412651.701       374483.16
     2413085.034       374339.41
#Sta/Elev= 30
       0  422.89    15.8  420.99    35.6  419.18    51.4   416.9      79   413.9
    94.8  411.58   106.6  409.07  114.28407.9564   130.4  404.97     178  398.57
   201.8  396.46   241.5  394.76   261.3  393.51   273.2  393.47   274.8 393.434
   281.2  393.29  284.83393.3172   316.9  394.38   324.8  394.07  337.97 394.648
   356.6  394.48  383.52394.9712  399.83395.6536     436  398.85  482.22405.5801
  492.61407.0512   511.4     409   531.3   409.8   547.2  411.58   594.8  415.71
#Mann= 11 ,-1 , 0
       0     .06       0  114.28     .08       0   241.5    .045       0
   273.2     .08       0   274.8     .12       0  284.83     .08       0
  337.97     .12       0  383.52     .08       0  399.83     .06       0
  482.22    .016       0  492.61     .08       0
#XS Ineff= 2 , 0
                          334.43          408.21
Permanent Ineff=
       F       F
Bank Sta=241.5,273.2
XS Rating Curve= 0 ,0
Exp/Cntr=0.3,0.1

Type RM Length L Ch R = 1 ,15943.1 ,370.4,365.6,360.7
XS GIS Cut Line= 2
     2412659.947      374650.695     2413138.463      374449.957
#Sta/Elev= 30
       0  420.81      16  418.69    27.9  416.46    39.9  413.49   56.34410.7977
    71.8     407    91.8  403.87    99.8  401.44   111.8  400.45  122.53 398.349
   127.7  397.24   143.7  395.32   159.7  392.31   175.6  390.87   183.6   388.6
   187.6  388.19   191.6  388.45   199.6  390.41   247.5  391.93   291.4  390.84
   331.3  391.65   359.2  393.98   403.2  399.51   419.1  401.98  457.35406.5078
     467  408.26  474.94408.7668     487  411.73     495  412.49   518.9  415.97
#Mann= 7 ,-1 , 0
       0     .06       0   56.34     .12       0  122.53     .06       0
   175.6    .045       0   199.6     .06       0  457.35     .08       0
  474.94     .06       0
Bank Sta=175.6,199.6
XS Rating Curve= 0 ,0
Exp/Cntr=0.3,0.1

Type RM Length L Ch R = 1 ,15577.5 ,330.2,338.6,346.4
XS GIS Cut Line= 2
     2412881.791      374926.488     2413275.777      374703.677
#Sta/Elev= 30
       0  408.07    23.8  406.79    67.5  400.21   115.1  395.61     127  394.74
   146.9  392.03   166.8  390.09   190.6  388.52   222.3   388.6   242.2  389.11
   246.2  389.06   250.1  388.17   254.1  386.72   258.1   385.9     262  385.86
     270  387.65   305.7  389.31   309.7     390   321.6  392.95   337.5  397.53
   345.4  398.93   365.3  401.46   377.2  403.26   385.1  403.79     397  405.22
     409  405.83  419.57407.0438   432.8  409.27   444.7  411.95   452.6  412.49
#Mann= 4 ,-1 , 0
       0     .06       0   250.1    .045       0     270     .06       0
  419.57     .08       0
Bank Sta=250.1,270
XS Rating Curve= 0 ,0
Exp/Cntr=0.3,0.1

Type RM Length L Ch R = 1 ,15238.9 ,262.1,268.9,275
XS GIS Cut Line= 2
     2413033.211      375171.528     2413424.921       375041.32
#Sta/Elev= 30
       0   402.5    15.9  400.83    23.8  399.69    39.7  397.97    75.4  394.33
  100.65392.0906   111.1  390.42  121.27 388.425     135  386.65   146.9  386.11
   174.6  386.66  199.15386.8219   206.4  386.74  214.06385.8907   218.3  385.05
   222.3  384.34   226.2  383.97   230.2  383.92   234.2  384.04   238.6  384.91
   242.1  385.82   246.1  386.46   265.9  387.54   297.7  391.88   329.4  397.46
   345.3  399.69   357.2  401.99   369.1  403.64     381  404.83   412.8  407.08
#Mann= 7 ,-1 , 0
       0     .06       0  100.65     .12       0  121.27     .06       0
  199.15     .12       0  214.06     .06       0   218.3    .045       0
   238.6     .06       0
Bank Sta=218.3,238.6
XS Rating Curve= 0 ,0
Exp/Cntr=0.3,0.1