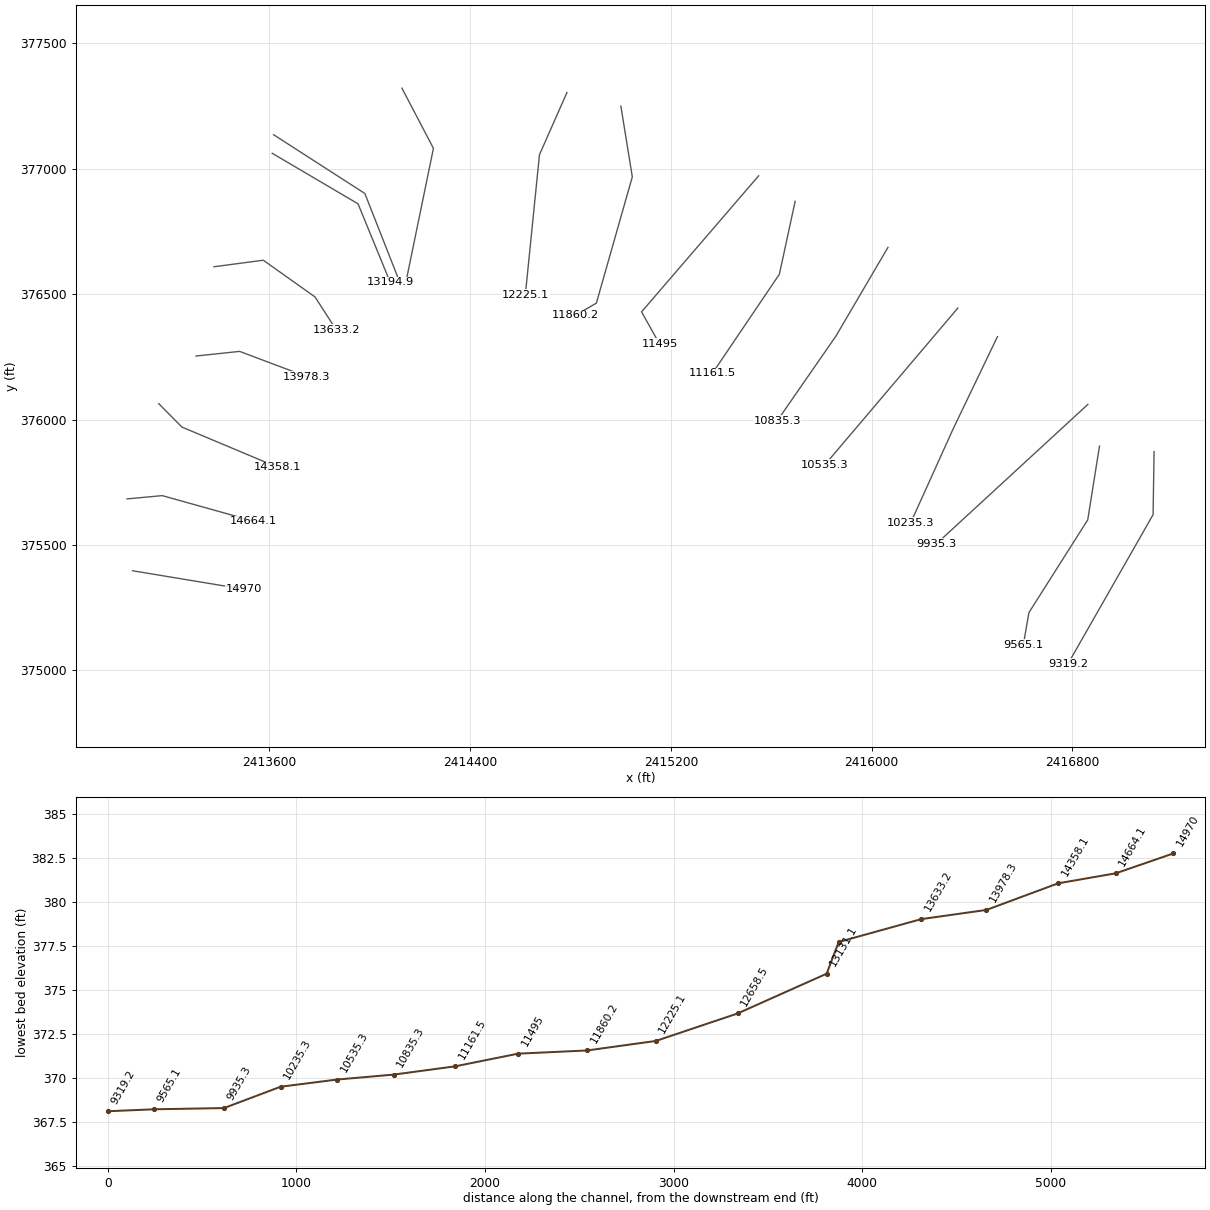
HEC-RAS study HOKERUN.prj: HOKERUN

--- HOKERUN.g01 (geometry) --- (continued)

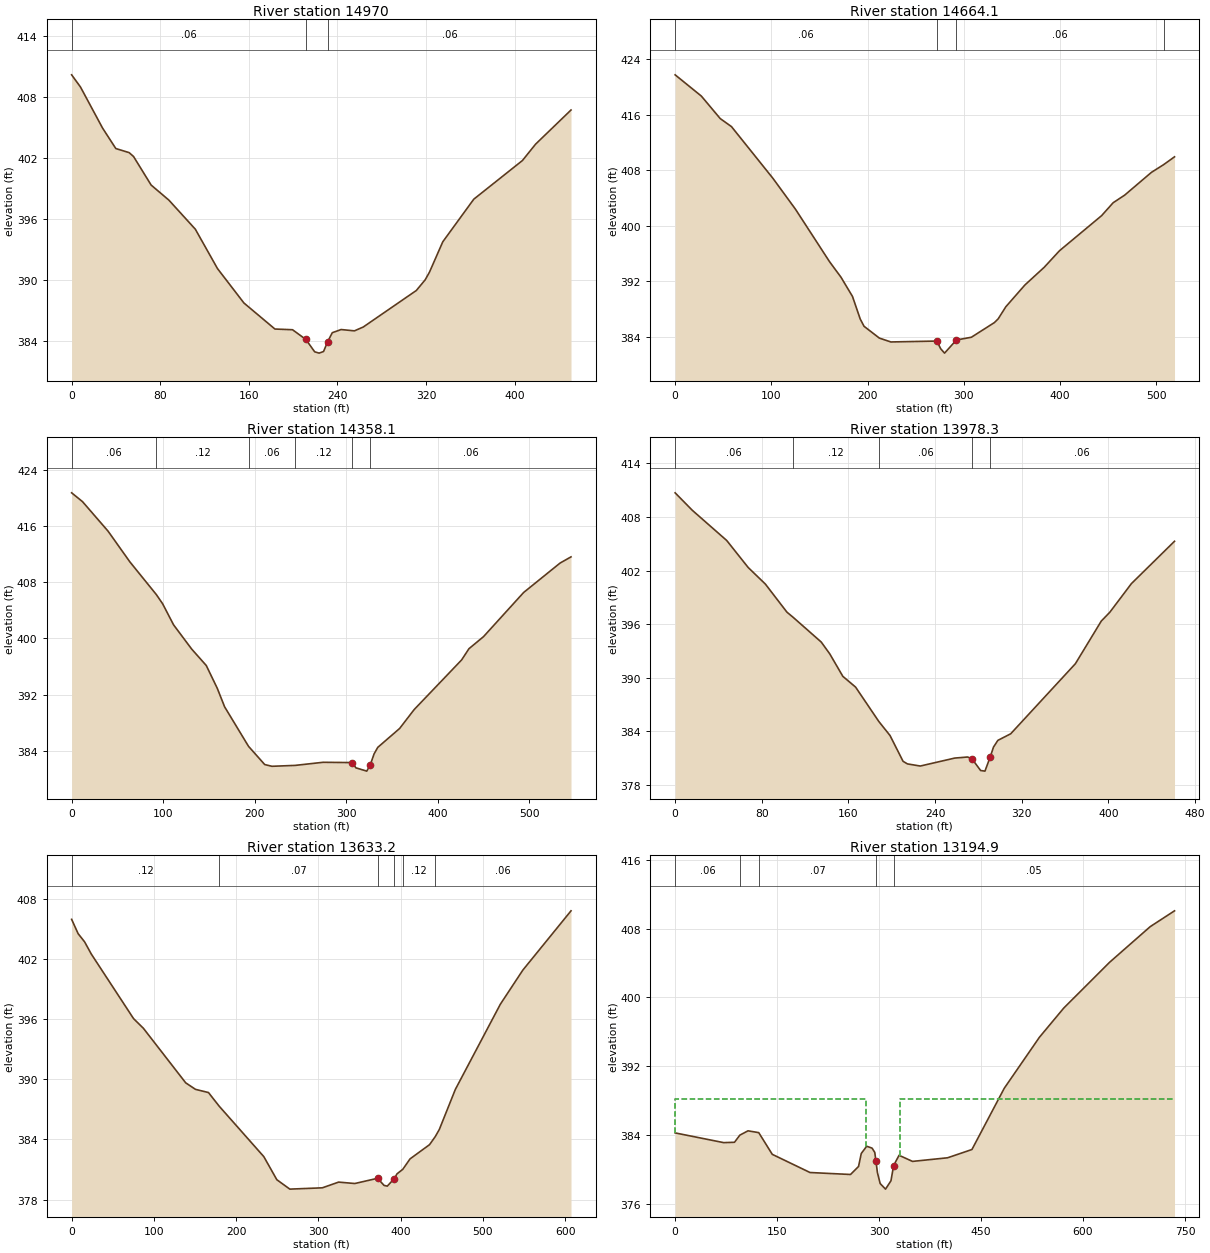
Type RM Length L Ch R = 1 ,14970   ,310,305.9,301.7
XS GIS Cut Line= 2
     2413054.913      375397.222     2413499.791      375323.438
#Sta/Elev= 30
       0  410.14       8  408.94    27.9  404.91    39.9  402.89    51.9  402.49
    55.9  402.11    71.8   399.3    87.8  397.82   111.7  394.96   131.7  391.09
   155.6   387.7   183.6  385.14   199.5  385.07   211.5  384.12   219.5   382.9
   223.5  382.77   227.5  382.93   231.3  383.91   235.4  384.78   243.4  385.09
   255.4  384.96   263.4  385.34   311.3  388.93   319.3  389.98   323.2  390.74
   335.2  393.72   363.2  397.91   407.1  401.71     419  403.32     451  406.68
#Mann= 3 ,-1 , 0
       0     .06       0   211.5    .045       0   231.3     .06       0
Bank Sta=211.5,231.3
XS Rating Curve= 0 ,0
Exp/Cntr=0.3,0.1

Type RM Length L Ch R = 1 ,14664.1 ,306,306,289
XS GIS Cut Line= 3
     2413033.211      375683.681     2413173.185      375696.702
     2413537.768      375594.705
#Sta/Elev= 30
       0  421.76    27.3  418.69    46.9  415.45    58.6  414.29   101.5  406.87
     125  402.41   160.5  394.83   172.5  392.57   184.4  389.81   192.4  386.57
   196.4  385.51   212.3  383.81   224.3  383.25   272.1  383.38   276.1  382.27
   280.1  381.64   292.4  383.53     308  383.93   331.9  386.04   335.8  386.57
   343.8  388.32   363.7  391.47   383.7  394.01   399.6   396.4   443.4  401.46
   455.4  403.32   467.4  404.42   495.2   407.7  507.84408.8072   519.2  409.94
#Mann= 4 ,-1 , 0
       0     .06       0   272.1    .045       0   292.4     .06       0
  507.84     .12       0
Bank Sta=272.1,292.4
XS Rating Curve= 0 ,0
Exp/Cntr=0.3,0.1

Type RM Length L Ch R = 1 ,14358.1 ,377.1,379.8,382.6
XS GIS Cut Line= 3
     2413159.079      376063.455      2413251.31      375970.139
     2413633.255      375809.549
#Sta/Elev= 30
       0  420.79    11.9  419.53    39.8  415.32    63.6  410.94   92.53406.2668
    99.4  404.96   111.3  401.96   131.2  398.48   147.1  396.14   159.1  392.89
   167.1  390.25  193.24 384.608   210.9  382.01   218.8  381.76  244.15381.8873
   274.6  382.33   306.5  382.29   310.5  381.54   322.4  381.07   326.2381.9725
   330.4  383.53   334.4  384.46   358.3  387.16   374.2  389.86     426  396.94
     434  398.54   449.9  400.26   493.7  406.56   533.6  410.77   545.5  411.65
#Mann= 6 ,-1 , 0
       0     .06       0   92.53     .12       0  193.24     .06       0
  244.15     .12       0   306.5    .045       0   326.2     .06       0
Bank Sta=306.5,326.2
XS Rating Curve= 0 ,0
Exp/Cntr=0.3,0.1

Type RM Length L Ch R = 1 ,13978.3 ,354.2,345.1,335.1
XS GIS Cut Line= 3
     2413307.734      376253.342     2413481.345      376271.788
     2413749.357      376170.877
#Sta/Elev= 30
       0   410.7    15.9  408.74    47.6  405.37    67.4  402.35    83.3  400.49
   103.2  397.35  109.05396.7586   134.9     394   142.8  392.67   154.8  390.17
   166.6  388.96  188.07385.1092   198.4  383.54   210.4  380.66   214.4  380.37
   226.3  380.13   258.1  381.02     270  381.14     274  380.94     282  379.63
     286  379.56   290.7  381.09   293.9  382.25   297.9     383   309.8  383.74
   369.5  391.58   393.4  396.35   401.3  397.34   421.2  400.54     461  405.28
#Mann= 5 ,-1 , 0
       0     .06       0  109.05     .12       0  188.07     .06       0
     274    .045       0   290.7     .06       0
Bank Sta=274,290.7
XS Rating Curve= 0 ,0
Exp/Cntr=0.3,0.1

Type RM Length L Ch R = 1 ,13633.2 ,436.6,438.3,441.9
XS GIS Cut Line= 4
     2413379.348      376609.245     2413575.746      376635.287
     2413781.909      376488.802     2413866.544      376357.509
#Sta/Elev= 30
       0  405.97     7.9  404.54    15.8  403.72    23.8  402.52    75.3  396.06
    87.2   395.1   138.7  389.65   150.6     389   166.4  388.68  179.39 387.321
   233.7  382.28   249.5  379.98   265.3  379.04   304.8  379.17   324.6  379.74
   344.3   379.6     372  380.12   379.9  379.41   383.8  379.34   391.8  380.05
   395.7  380.57  402.63381.0151   411.5  382.06   435.2  383.48  442.21384.2922
   447.1     385   466.6     389   521.3   397.5   548.6   400.9   607.2  406.82
#Mann= 6 ,-1 , 0
       0     .12       0  179.39     .07       0     372    .045       0
   391.8     .07       0  402.63     .12       0  442.21     .06       0
Bank Sta=372,391.8
XS Rating Curve= 0 ,0
Exp/Cntr=0.3,0.1

Type RM Length L Ch R = 1 ,13194.9 ,65.3,63.8,59.5
XS GIS Cut Line= 3
     2413611.411      377061.588     2413953.313      376860.124
     2414081.351      376547.624
#Sta/Elev= 30
       0  384.27    71.4  383.14    87.3  383.18    95.2  384.01   107.2  384.51
     123   384.3   142.9  381.78   198.4  379.67     258  379.44   269.8  380.37
   273.8  381.88   281.8  382.72   289.7   382.5   293.7     382   295.3  381.04
   297.6  379.65   301.6  378.39   309.5  377.74   317.5  378.71   321.4  380.48
   329.4  381.67   349.2  380.96   400.8  381.38   436.6  382.34   484.2  389.46
   535.9  395.38   571.7  398.77   639.2  404.09   698.8  408.22   734.6  410.06
#Mann= 5 ,-1 , 0
       0     .06       0    95.2    .016       0     123     .07       0
   295.3    .045       0   321.4     .05       0
#XS Ineff= 2 , 0
          281.46  388.16   330.9          388.21
Permanent Ineff=
       F       F
Bank Sta=295.3,321.4
XS Rating Curve= 0 ,0
Exp/Cntr=0.3,0.1

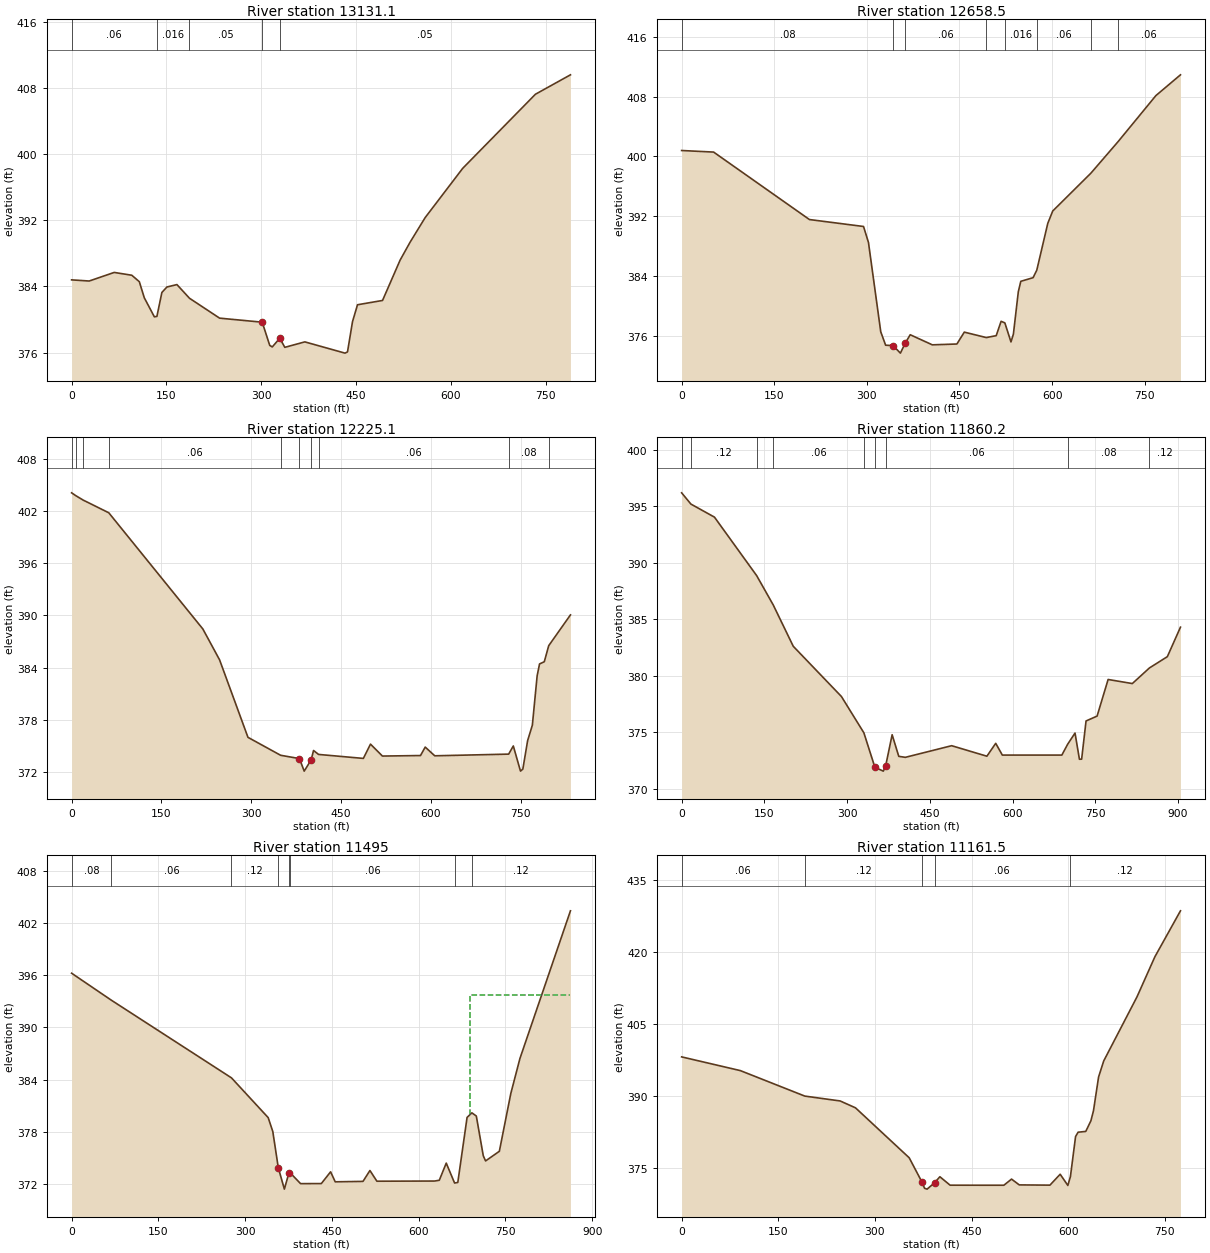
Type RM Length L Ch R = 1 ,13131.1 ,519.6,472.6,423.6
XS GIS Cut Line= 3
     2413616.961      377135.591      2413980.44      376901.357
     2414110.927      376569.472
#Sta/Elev= 30
       0   384.8    27.8  384.66    67.4   385.7    95.2  385.36   107.1  384.58
     115  382.63   130.9  380.33   134.9  380.38   142.8  383.28   150.8  383.94
   166.6  384.23   186.4  382.58   234.1  380.17   301.5  379.68   313.4  376.87
   317.4  376.69   329.3  377.74   337.2  376.64   368.9   377.3   432.4  375.94
   436.4  376.09   444.3  379.75   452.2  381.79   491.8  382.31   519.6  387.19
   535.4  389.36   559.2  392.33   618.6  398.29   733.6  407.25     789   409.6
#Mann= 5 ,-1 , 0
       0     .06       0   134.9    .016       0   186.4     .05       0
   301.5    .045       0   329.3     .05       0
Bank Sta=301.5,329.3
XS Rating Curve= 0 ,0
Exp/Cntr=0.3,0.1

Type RM Length L Ch R = 1 ,12658.5 ,429.5,433.4,437.2
XS GIS Cut Line= 3
     2414128.184        377321.3     2414253.684      377081.382
     2414145.545      376555.241
#Sta/Elev= 30
       0   400.8    51.8  400.59     207  391.56   294.6  390.63   302.6  388.49
   322.5  376.53   330.4  374.74   342.4  374.69   354.3  373.68   362.3  375.04
   370.2  376.14     406  374.79   445.8   374.9   457.8  376.49  493.44375.7616
   509.5  376.02   517.4  377.94  523.47377.7288   533.4  375.18   537.3  376.22
   545.3  381.91   549.3  383.29   569.2  383.78  575.18384.7776     593  391.05
     601   392.7  662.86397.7698  706.85401.9856   768.1  408.15   807.9  410.93
#Mann= 8 ,-1 , 0
       0     .08       0   342.4    .045       0   362.3     .06       0
  493.44     .08       0  523.47    .016       0  575.18     .06       0
  662.86     .12       0  706.85     .06       0
Bank Sta=342.4,362.3
XS Rating Curve= 0 ,0
Exp/Cntr=0.3,0.1

Type RM Length L Ch R = 1 ,12225.1 ,371.6,364.9,358.3
XS GIS Cut Line= 4
     2414785.736      377303.939      2414676.24      377055.986
      2414660.94      376904.263     2414619.854      376496.829
#Sta/Elev= 30
       0  404.08    6.97403.7535   19.16403.2515   62.08401.7889   219.2  388.44
   247.1   384.9   294.5     376  349.03373.9404   380.5  373.56   388.4  372.12
   400.1  373.42     404  374.49  412.38374.0371   487.2  373.58   499.1  375.22
     519  373.85   582.6  373.91   590.5  374.88   606.4  373.88  729.82374.0728
   737.6  375.01   749.6  372.12   753.5  372.35   761.5  375.62   769.4   377.4
   777.4  383.07   781.4  384.43   789.3  384.68  796.73386.5262     833  390.06
#Mann= 10 ,-1 , 0
       0     .06       0    6.97     .12       0   19.16     .08       0
   62.08     .06       0  349.03     .08       0   380.5    .045       0
   400.1     .08       0  412.38     .06       0  729.82     .08       0
  796.73     .06       0
Bank Sta=380.5,400.1
XS Rating Curve= 0 ,0
Exp/Cntr=0.3,0.1

Type RM Length L Ch R = 1 ,11860.2 ,381.6,365.2,348.7
XS GIS Cut Line= 4
     2415000.579      377249.686     2415046.152      376967.567
     2414902.923      376464.095     2414820.458      376416.352
#Sta/Elev= 30
       0  396.21   16.85395.2137    59.5  394.06  136.06388.8822  166.04386.2928
   202.4  382.63   289.8  378.18  330.48374.9676   350.4  371.92   365.7  371.58
   369.7  371.99   381.7   374.8   393.7  372.89   405.6   372.8   489.6  373.83
   553.5   372.9   569.5  374.04   581.5     373   689.4     373  699.99373.9618
   713.3  374.95   721.3  372.63   725.3  372.64   733.3  376.02   753.3  376.45
   773.3  379.69   817.2  379.33  848.33380.7156   880.7  381.71   904.5  384.32
#Mann= 9 ,-1 , 0
       0     .06       0   16.85     .12       0  136.06     .08       0
  166.04     .06       0  330.48     .08       0   350.4    .045       0
   369.7     .06       0  699.99     .08       0  848.33     .12       0
Bank Sta=350.4,369.7
XS Rating Curve= 0 ,0
Exp/Cntr=0.3,0.1

Type RM Length L Ch R = 1 ,11495   ,329,333.5,337.6
XS GIS Cut Line= 3
     2415549.625      376971.908     2415083.045      376429.373
     2415154.659      376301.335
#Sta/Elev= 30
       0  396.22   68.42 393.129  276.38384.1881   339.8  379.62   347.8  378.02
   357.3  373.85   367.8   371.4   375.8   373.3   378.1 373.254   395.8  372.03
   431.7  372.04   447.7  373.39   455.7  372.24   503.7  372.29   515.7  373.54
   527.7  372.31   627.6  372.33   635.6  372.42   647.6  374.39  662.03372.1006
   667.6  372.17   683.6  379.64   691.9  380.17   699.6   379.8   711.6  375.24
   715.6  374.64   739.4  375.75   759.2  382.39     775  386.42   862.3  403.39
#Mann= 8 ,-1 , 0
       0     .08       0   68.42     .06       0  276.38     .12       0
   357.3    .045       0   375.8     .12       0   378.1     .06       0
  662.03     .08       0   691.9     .12       0
#XS Ineff= 2 , 0
                          688.52          393.66
Permanent Ineff=
       F       F
Bank Sta=357.3,375.8
XS Rating Curve= 0 ,0
Exp/Cntr=0.3,0.1

Type RM Length L Ch R = 1 ,11161.5 ,324,326.2,326
XS GIS Cut Line= 3
     2415695.024      376869.911      2415632.09      376579.113
     2415365.163      376184.147
#Sta/Elev= 30
       0  398.23    91.2  395.37  191.16390.0619     246  389.05   269.8  387.62
   353.2  377.21     373  372.15     377  370.86     381  370.68   392.9  372.05
   400.8  373.26   416.7   371.5   500.1  371.49     512  372.77     524  371.56
   571.6  371.51   587.5  373.78   599.4  371.45  602.34 372.795   603.4  373.28
   611.4  381.63   615.3  382.54   627.2   382.7   635.2  384.92   639.2  387.02
   647.1  394.04   655.1  397.39   706.7  410.73   734.5  419.09   774.2  428.66
#Mann= 5 ,-1 , 0
       0     .06       0  191.16     .12       0     373    .045       0
   392.9     .06       0  602.34     .12       0
Bank Sta=373,392.9
XS Rating Curve= 0 ,0
Exp/Cntr=0.3,0.1

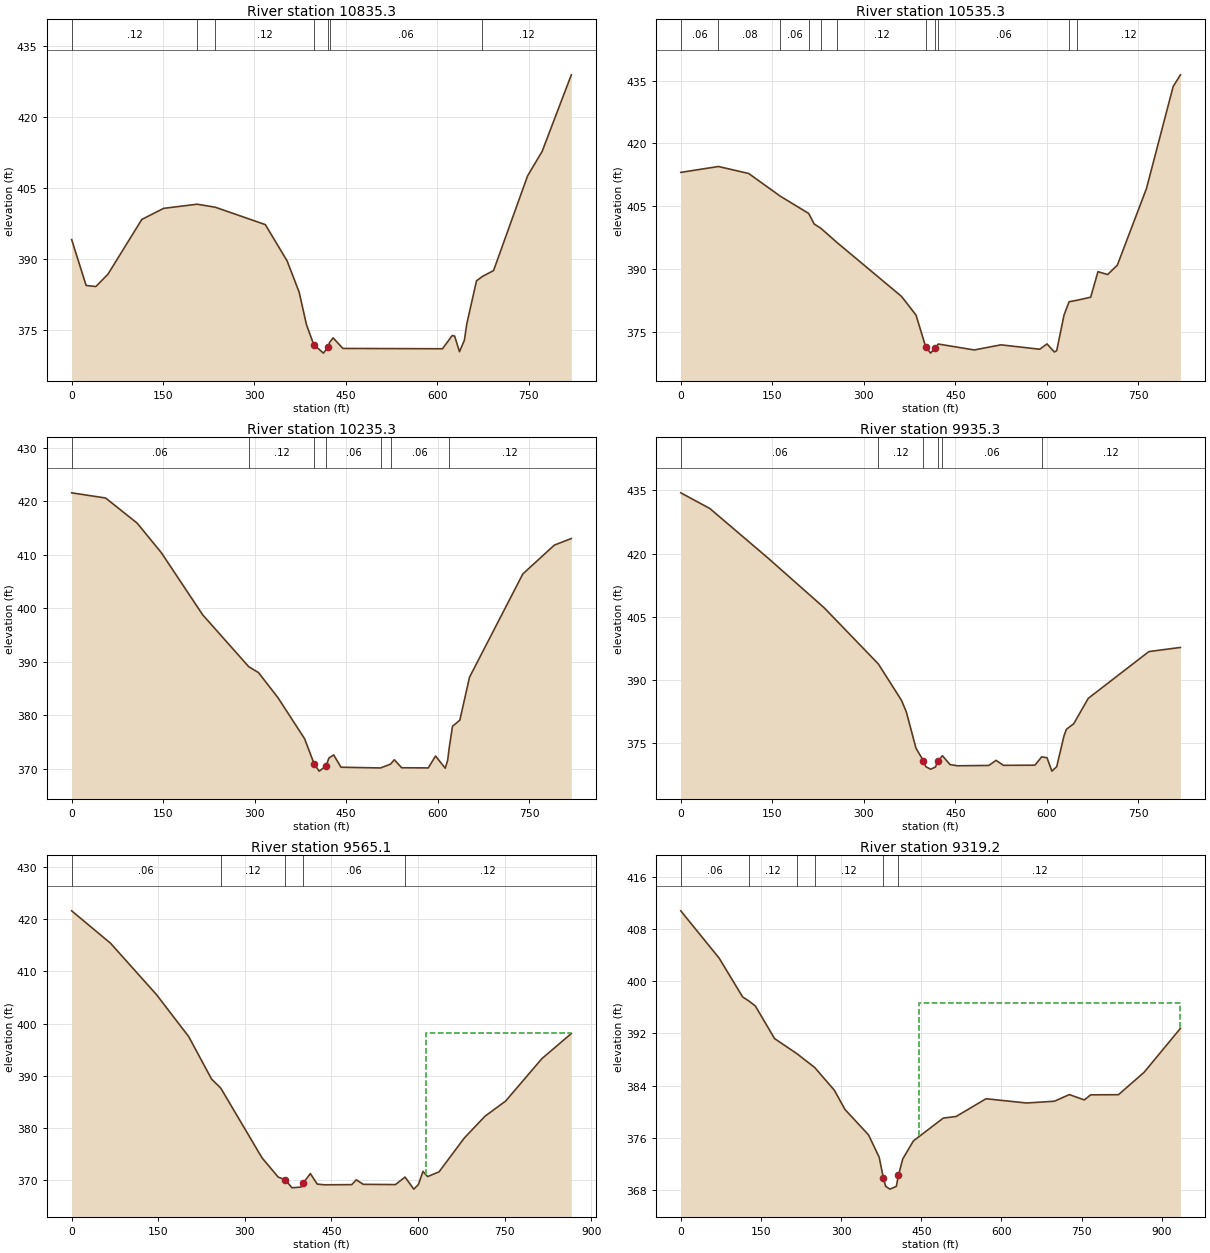
Type RM Length L Ch R = 1 ,10835.3 ,306.5,300,296.3
XS GIS Cut Line= 3
     2416064.862       376686.44     2415857.887      376333.369
     2415624.074      375995.563
#Sta/Elev= 30
       0  394.17    23.8  384.48    39.7  384.26    59.6  386.86   115.2  398.42
     151  400.75  206.03401.6285     236 400.982   317.9  397.32   353.6  389.68
   373.5  383.04   385.4  376.22   397.3  372.03   413.2  370.21   421.2  371.54
  423.41372.4903   429.2  373.42   445.2   371.2   608.7  371.13   624.6  373.92
   628.6  373.81   636.6  370.51   644.6  372.93   648.6  376.42   664.5  385.46
  674.24386.3909   692.5  387.63   748.3   407.6   772.2  412.76   820.1  428.92
#Mann= 7 ,-1 , 0
       0     .12       0  206.03     .06       0     236     .12       0
   397.3    .045       0   421.2     .12       0  423.41     .06       0
  674.24     .12       0
Bank Sta=397.3,421.2
XS Rating Curve= 0 ,0
Exp/Cntr=0.3,0.1

Type RM Length L Ch R = 1 ,10535.3 ,290.4,300,310.5
XS GIS Cut Line= 3
     2416343.215      376444.464     2416078.397      376132.115
     2415813.579      375819.767
#Sta/Elev= 30
       0  413.09   61.69414.4991   111.3  412.83  163.13407.4128  209.69403.2867
   218.7  400.76  229.51399.7591  256.25396.3287   361.8  383.48   385.6  379.02
   401.6  371.36   409.5  369.93     417  371.18   422.1372.1038   481.1  370.69
   524.8  371.91   588.4  370.86   600.3  372.13   612.3  370.21   616.2  370.52
   628.2  379.02  636.54382.2041  649.26382.5468   671.9  383.29   683.8  389.38
   699.7   388.7   715.6  390.94   763.3  409.23   807.1  433.61     819  436.39
#Mann= 11 ,-1 , 0
       0     .06       0   61.69     .08       0  163.13     .06       0
  209.69     .12       0  229.51     .06       0  256.25     .12       0
   401.6    .045       0     417     .12       0   422.1     .06       0
  636.54     .08       0  649.26     .12       0
Bank Sta=401.6,417
XS Rating Curve= 0 ,0
Exp/Cntr=0.3,0.1

Type RM Length L Ch R = 1 ,10235.3 ,314.2,300,284.8
XS GIS Cut Line= 3
     2416501.215       376330.74     2416323.902       375961.32
     2416155.376      375588.157
#Sta/Elev= 30
       0  421.53    55.7  420.56   107.4  415.87   147.2  410.32   214.8  398.74
  290.42389.0276   306.3  387.94   338.2  383.26   381.9  375.58   397.8  370.82
   405.8  369.52   417.3   370.5   421.7  371.95   429.6  372.55   441.6  370.25
  506.48370.1132  523.01370.8367     529  371.65     541  370.15   584.7  370.12
   596.6  372.35   612.5  370.07   616.5  371.55  619.12373.9473   624.4   377.9
   636.4  379.04   652.3  387.07   739.7  406.37   791.4  411.76   819.2  412.99
#Mann= 7 ,-1 , 0
       0     .06       0  290.42     .12       0   397.8    .045       0
   417.3     .06       0  506.48     .08       0  523.01     .06       0
  619.12     .12       0
Bank Sta=397.8,417.3
XS Rating Curve= 0 ,0
Exp/Cntr=0.3,0.1

Type RM Length L Ch R = 1 ,9935.3  ,364,370.2,379.6
XS GIS Cut Line= 3
     2416861.579      376060.555     2416560.374      375783.128
     2416259.169      375505.701
#Sta/Elev= 30
       0  434.44    47.7  430.71   143.1  418.93   234.6  407.19  323.88393.7757
   361.8  385.13   369.7  382.39   385.6  373.74   397.6  370.82   401.6  369.38
   409.5  368.76   417.4  369.28   421.4  370.66  428.86371.9703   441.3  369.87
   453.2  369.58   504.9  369.66   516.8  370.87   528.8  369.69   580.5  369.72
  591.55371.6972   600.3   371.5   608.3  368.31   616.2  369.36   628.2  376.72
   632.1  378.25   644.1  379.57   667.9   385.6   767.3  396.72     819   397.7
#Mann= 6 ,-1 , 0
       0     .06       0  323.88     .12       0   397.6    .045       0
   421.4     .12       0  428.86     .06       0  591.55     .12       0
Bank Sta=397.6,421.4
XS Rating Curve= 0 ,0
Exp/Cntr=0.3,0.1

Type RM Length L Ch R = 1 ,9565.1  ,241.1,246,245.4
XS GIS Cut Line= 4
     2416907.777      375894.365     2416860.902      375600.094
     2416626.527      375230.303     2416604.392      375102.698
#Sta/Elev= 30
       0  421.61    67.5  415.38     147  405.53   202.6  397.51   242.4  389.33
  258.22387.6154   329.8  374.22   357.7  370.55   369.6  370.06   381.6   368.5
   397.5  368.64   401.5  369.48   413.4  371.22   425.3  369.21   437.3  369.07
     485   369.1     493  370.02     505  369.16   560.7  369.11  577.38370.5503
   592.5  368.24   600.5  369.12   608.4  371.64   616.4  370.65   636.3  371.56
   680.1  378.06   715.9  382.23   751.5  385.12   814.3  393.26   865.3  398.08
#Mann= 5 ,-1 , 0
       0     .06       0  258.22     .12       0   369.6    .045       0
   401.5     .06       0  577.38     .12       0
#XS Ineff= 2 , 0
                          614.12          398.21
Permanent Ineff=
       F       F
Bank Sta=369.6,401.5
XS Rating Curve= 0 ,0
Exp/Cntr=0.3,0.1

Type RM Length L Ch R = 1 ,9319.2  ,80.6,81.9,91.5
XS GIS Cut Line= 3
     2417125.225       375872.23     2417121.319      375620.928
     2416782.777      375027.178
#Sta/Elev= 30
       0  410.78    71.8  403.53   115.7  397.59  127.71 396.949   139.6  396.19
   175.5   391.2  216.67 388.926  250.69386.7603   287.3  383.29   307.3  380.33
   351.3  376.44   371.2  373.02   379.2   369.8   383.2  368.57   391.2  368.13
   403.2  368.54   407.2  370.22   415.2  372.74   435.2  375.52   491.2  379.02
   515.1  379.26   571.1  381.98     647  381.33     699   381.6     727  382.62
     755   381.8   766.9  382.58   818.9   382.6   866.9  386.04   934.8  392.77
#Mann= 6 ,-1 , 0
       0     .06       0  127.71     .12       0  216.67     .06       0
  250.69     .12       0   379.2    .045       0   407.2     .12       0
#XS Ineff= 2 , 0
                          446.41          396.73
Permanent Ineff=
       F       F
Bank Sta=379.2,407.2
XS Rating Curve= 0 ,0
Exp/Cntr=0.3,0.1