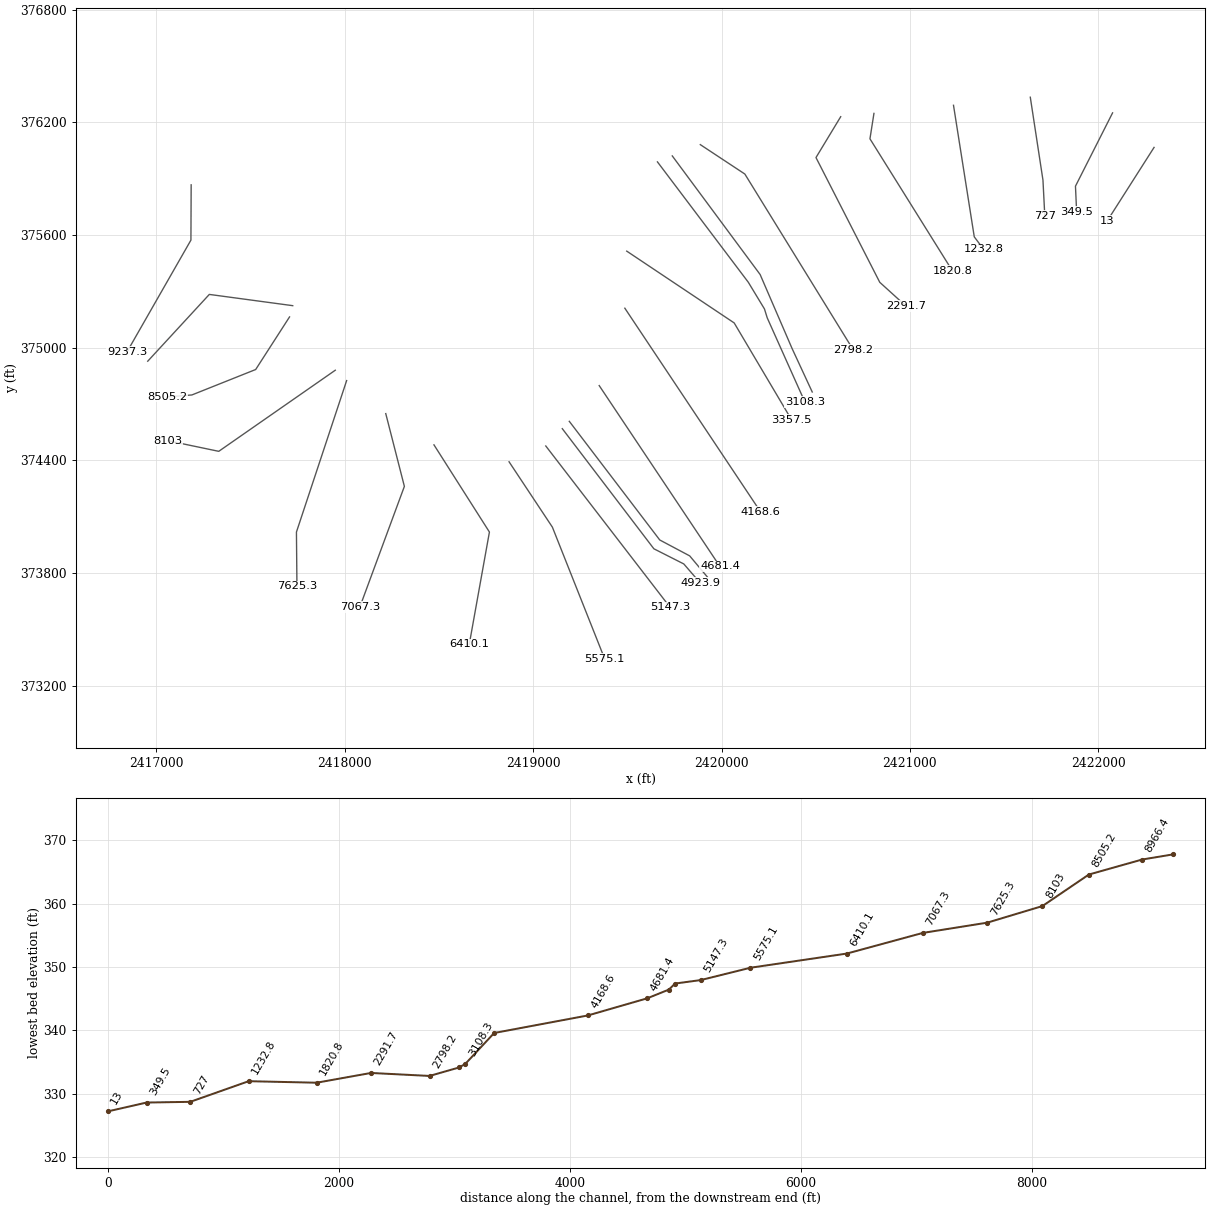
HEC-RAS study HOKERUN.prj: HOKERUN

--- HOKERUN.g01 (geometry) --- (continued)

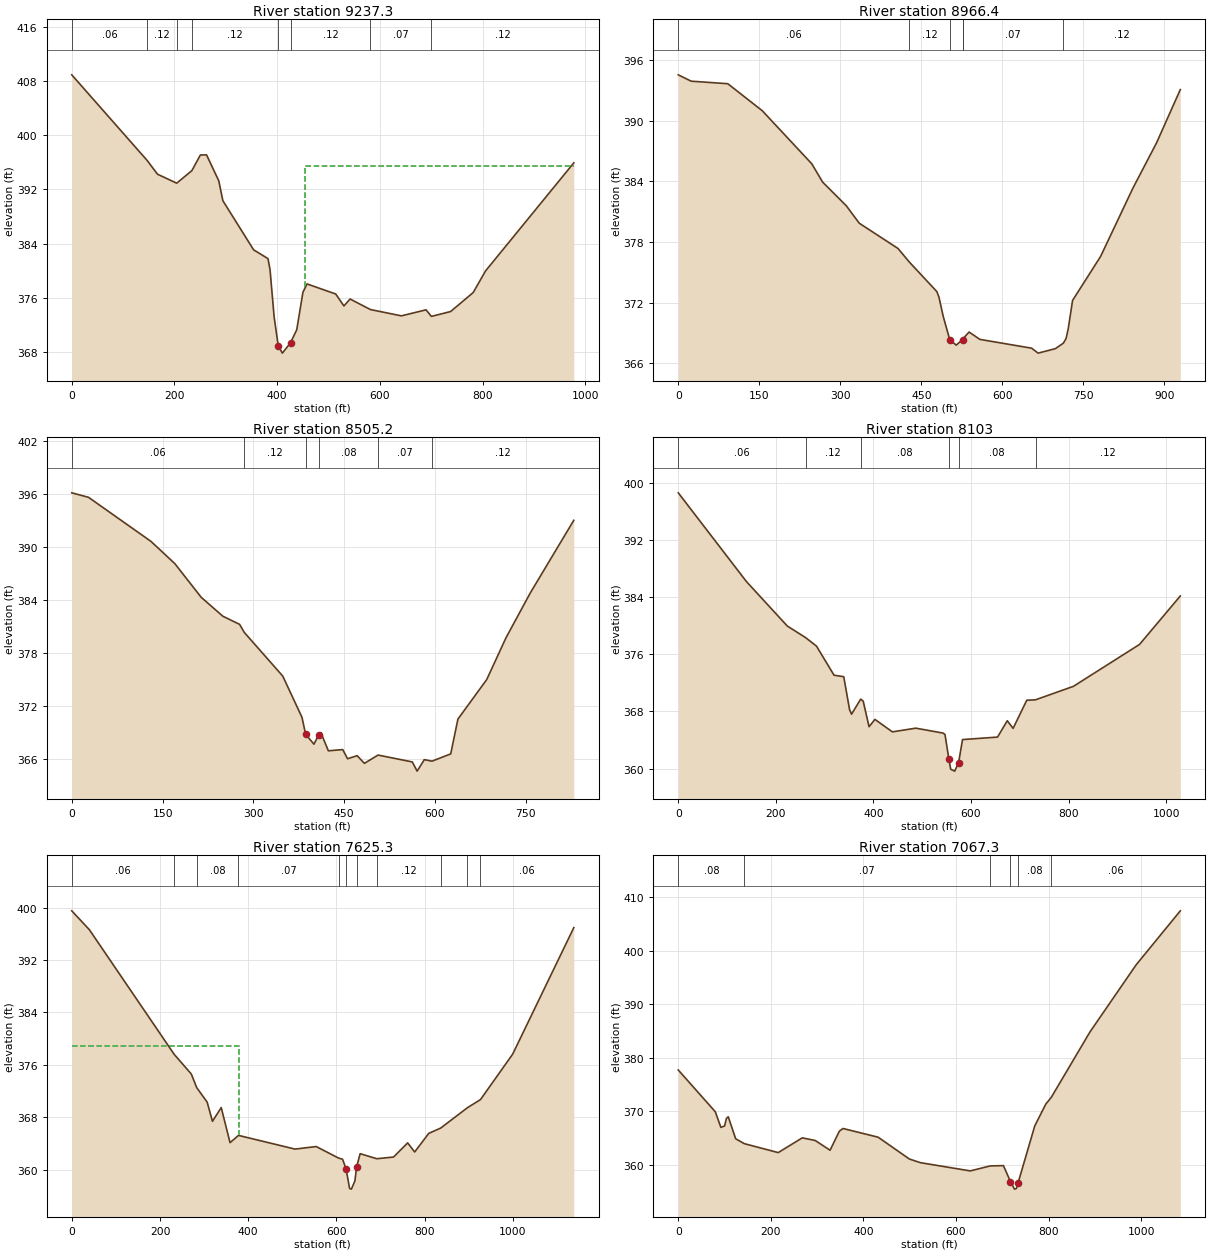
Type RM Length L Ch R = 1 ,9237.3  ,281.4,270.9,253
XS GIS Cut Line= 3
     2417185.121      375867.021     2417183.819       375572.75
     2416845.277         374979.
#Sta/Elev= 30
       0  408.95  146.68396.3042     167  394.26  204.41392.9328  233.93394.7897
   250.5   397.1   262.5  397.12   286.3  393.29   294.3  390.34   354.2  383.08
   382.2  381.78   386.2  380.13   394.2  373.12   402.2  368.88   410.2  367.81
   426.2  369.35   438.2  371.27   450.2   376.8   458.2  378.04   514.1  376.55
   530.1  374.78   542.1  375.81  581.73374.2508     642  373.32     690  374.21
  700.44 373.239   737.9  373.96   781.9  376.77   805.9  379.96   977.8  395.94
#Mann= 8 ,-1 , 0
       0     .06       0  146.68     .12       0  204.41     .08       0
  233.93     .12       0   402.2    .045       0   426.2     .12       0
  581.73     .07       0  700.44     .12       0
#XS Ineff= 2 , 0
                          455.23          395.46
Permanent Ineff=
       F       F
Bank Sta=402.2,426.2
XS Rating Curve= 0 ,0
Exp/Cntr=0.3,0.1

Type RM Length L Ch R = 1 ,8966.4  ,478.3,461.2,444
XS GIS Cut Line= 3
     2417724.183      375223.792     2417281.475      375283.688
     2416954.652      374928.219
#Sta/Elev= 30
       0  394.56    23.9  393.93    91.7  393.68   155.6     391   247.3  385.74
   267.2  383.94   311.1  381.59   335.1  379.86   406.8  377.36  428.08375.9996
   478.7  373.09   482.7  372.54   490.6  370.63   502.6  368.34   514.6  367.78
   526.6  368.34   527.4 368.432   538.5  369.08   558.5  368.35   654.3  367.48
   666.2  366.99   698.2  367.43  713.06367.9818   718.1  368.44   722.1  369.41
   730.1  372.21     782  376.57   841.8  383.33   885.7  387.83   929.6   393.1
#Mann= 6 ,-1 , 0
       0     .06       0  428.08     .12       0   502.6    .045       0
   526.6     .12       0   527.4     .07       0  713.06     .12       0
Bank Sta=502.6,526.6
XS Rating Curve= 0 ,0
Exp/Cntr=0.3,0.1

Type RM Length L Ch R = 1 ,8505.2  ,393.2,402.2,407.6
XS GIS Cut Line= 4
     2417707.256      375163.896     2417527.569      374883.948
     2417189.027      374748.532     2417057.517      374738.115
#Sta/Elev= 30
       0  396.13    27.7  395.62   130.7  390.64   170.3  388.11   213.8   384.3
   249.5  382.16   277.2  381.24  284.91380.3292   348.5  375.38   380.2  370.72
   386.3  368.79     400  367.67     408  368.74   411.9   368.9   423.8  366.92
   447.6  367.06   455.5  366.02   471.4  366.37   483.3   365.5  505.89366.4385
   562.5  365.66   570.4  364.62   582.3  365.92  594.95365.7481   625.9  366.57
   637.8  370.51   685.4  374.99   717.3  379.73   757.2  384.78   829.2  393.02
#Mann= 6 ,-1 , 0
       0     .06       0  284.91     .12       0   386.3    .045       0
     408     .08       0  505.89     .07       0  594.95     .12       0
Bank Sta=386.3,408
XS Rating Curve= 0 ,0
Exp/Cntr=0.3,0.1

Type RM Length L Ch R = 1 ,8103    ,453.2,477.7,502.1
XS GIS Cut Line= 3
     2417950.068      374880.138     2417331.553      374448.422
     2417062.456      374504.846
#Sta/Elev= 30
       0  398.63   139.7   386.2   223.5  379.97  261.04378.3462   283.4  377.15
   319.3  373.08   339.2  372.87   351.2  368.25   355.2  367.62  374.01369.7265
   379.1  369.45   391.1  365.86   403.1  366.89     439  365.14   486.9  365.66
   542.8  364.97   546.8  364.77   554.7  361.35   558.5   359.9   566.7  359.64
   574.7  360.84   582.7  364.06   654.5  364.41   674.5   366.7   686.4  365.63
   714.4  369.57  732.34 369.631   810.1  371.52   945.6  377.39  1029.2  384.18
#Mann= 6 ,-1 , 0
       0     .06       0  261.04     .12       0  374.01     .08       0
   554.7    .045       0   574.7     .08       0  732.34     .12       0
Bank Sta=554.7,574.7
XS Rating Curve= 0 ,0
Exp/Cntr=0.3,0.1

Type RM Length L Ch R = 1 ,7625.3  ,549.6,558,606
XS GIS Cut Line= 3
     2418010.303      374824.922      2417743.88      374018.735
     2417746.555      373729.767
#Sta/Elev= 30
       0   399.5    39.9  396.62  232.27377.5858   271.1  374.58  283.16372.5184
   306.9   370.3   318.9  367.37   338.8  369.47   358.8  364.11  377.86365.2206
   506.2  363.13   554.1  363.52   604.7 361.764   613.9  361.58   621.8   360.1
   629.8  357.12   633.8  357.02   641.8  358.27   645.8  360.45   653.7  362.43
  691.48  361.66   729.5  361.92   761.4  364.08   777.3  362.69   809.2  365.53
  836.24366.3384  896.93  369.45  926.45370.6854   999.5  377.63    1138  396.93
#Mann= 11 ,-1 , 0
       0     .06       0  232.27     .12       0  283.16     .08       0
  377.86     .07       0   604.7     .08       0   621.8    .045       0
   645.8     .08       0  691.48     .12       0  836.24     .06       0
  896.93     .08       0  926.45     .06       0
#XS Ineff= 2 , 0
          378.31  378.83
Permanent Ineff=
       F       F
Bank Sta=621.8,645.8
XS Rating Curve= 0 ,0
Exp/Cntr=0.3,0.1

Type RM Length L Ch R = 1 ,7067.3  ,650.3,657.3,648.3
XS GIS Cut Line= 3
     2418217.937      374649.212     2418316.796       374261.79
     2418080.316      373619.411
#Sta/Elev= 30
       0   377.7      80  369.88      92  366.96     100  367.22     104  368.63
     108  368.94     124  364.82  142.84 363.905   215.9  362.24   267.9     365
   295.9   364.5   327.9  362.68   347.9  366.24   355.8  366.75   431.7  365.12
   499.3  361.03   523.2  360.35   630.7  358.81  673.72359.7427   702.3   359.8
   717.6  356.81   726.2   355.4   730.2   355.5   734.1   356.6     770  367.23
   793.8  371.31  805.76372.5851   889.4  384.84   988.8  397.36  1084.4  407.49
#Mann= 6 ,-1 , 0
       0     .08       0  142.84     .07       0  673.72     .08       0
   717.6    .045       0   734.1     .08       0  805.76     .06       0
Bank Sta=717.6,734.1
XS Rating Curve= 0 ,0
Exp/Cntr=0.3,0.1

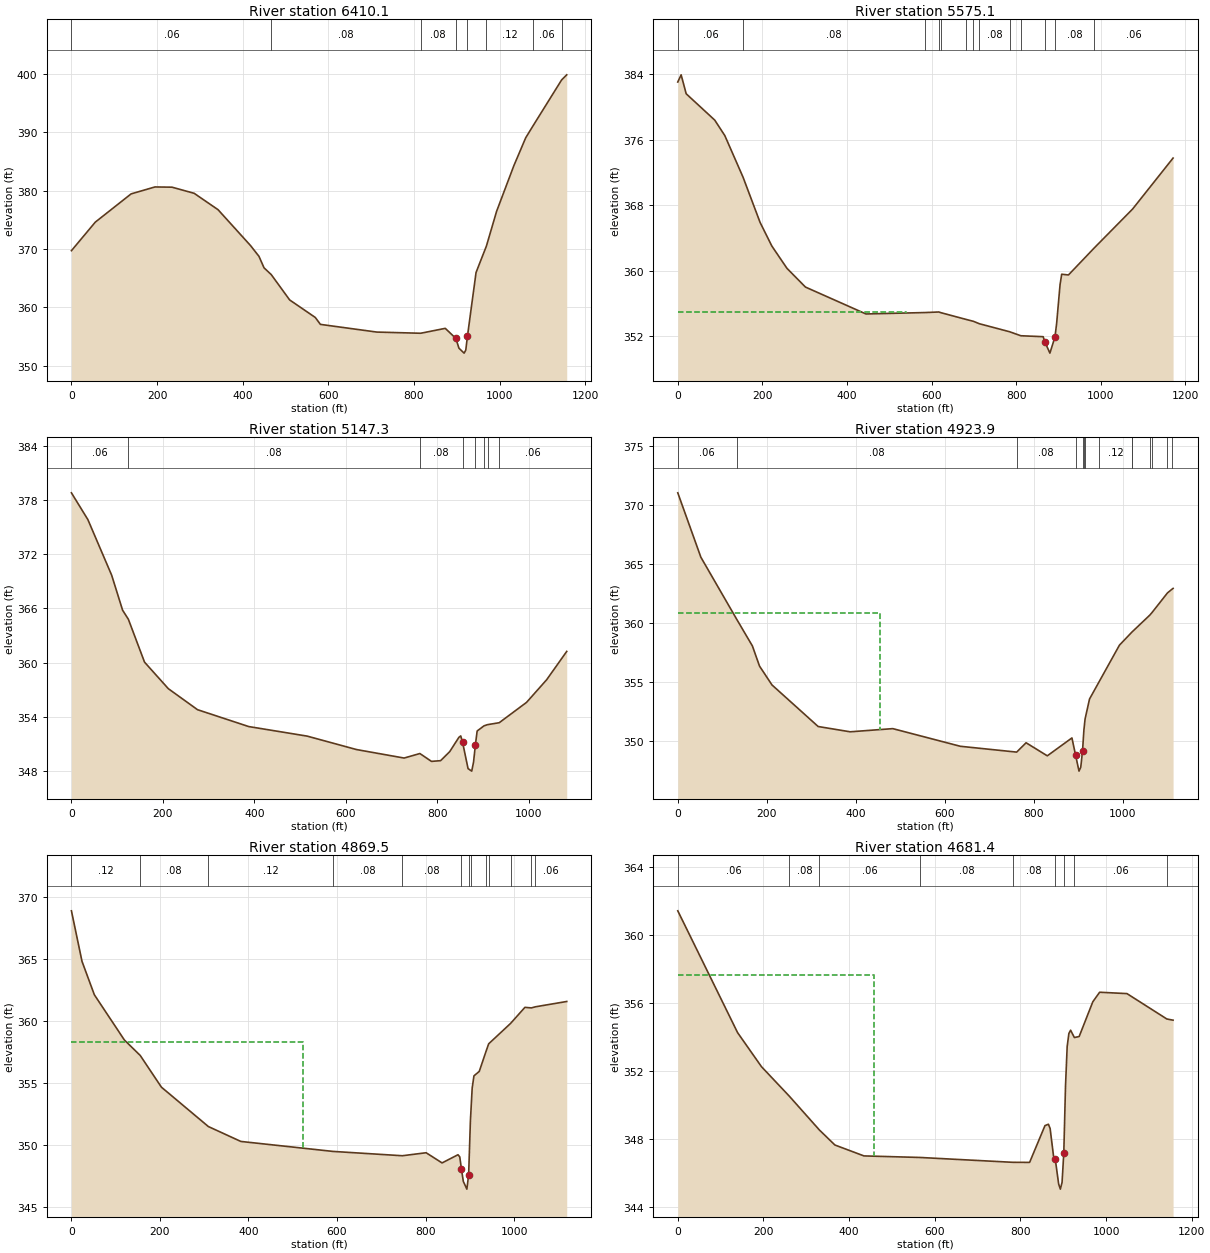
Type RM Length L Ch R = 1 ,6410.1  ,752.4,835,791.1
XS GIS Cut Line= 3
     2418473.861      374482.862     2418768.185      374018.735
     2418661.114      373420.783
#Sta/Elev= 30
       0  369.71    55.8  374.61   139.4  379.45   195.1  380.64     235   380.6
   286.7  379.55   342.5  376.74   418.2   370.6   438.1  368.74     450  366.76
  466.71365.6144   509.8  361.26   569.6  358.26   581.6  357.07   713.4  355.75
  815.82355.5482   873.3  356.39   897.9  354.67   905.3  352.98   917.3  352.14
   921.2  352.66   925.2   355.1   945.2  365.97  969.41370.5114   993.2  376.46
  1033.2  384.23  1061.1  389.06 1077.57391.0376    1145398.9877    1157  399.87
#Mann= 8 ,-1 , 0
       0     .06       0  466.71     .08       0  815.82     .08       0
   897.9    .045       0   925.2     .08       0  969.41     .12       0
 1077.57     .06       0    1145     .12       0
Bank Sta=897.9,925.2
XS Rating Curve= 0 ,0
Exp/Cntr=0.3,0.1

Type RM Length L Ch R = 1 ,5575.1  ,411.4,427.8,440.9
XS GIS Cut Line= 3
     2418872.424      374392.706     2419102.387      374044.777
     2419379.946      373343.575
#Sta/Elev= 30
       0  383.06     7.9  383.94    19.9  381.62    87.4   378.4   111.2  376.51
  154.29371.4244   194.6  365.89   222.4     363   258.2  360.27   301.9  357.98
     445  354.69  585.44354.8637  617.39354.9322  621.97354.8497   681.3354.0287
  698.93353.7931  713.25353.4934  784.45352.5174  811.27352.0257     864  351.91
   867.9  351.29   879.9   349.9   891.9  351.87   895.9  353.56   903.9  358.26
   907.8  359.55   923.8  359.46  985.09362.7813  1075.4  367.52  1171.2  373.76
#Mann= 13 ,-1 , 0
       0     .06       0  154.29     .08       0  585.44     .06       0
  617.39     .08       0  621.97     .06       0   681.3     .08       0
  698.93     .06       0  713.25     .08       0  784.45     .12       0
  811.27     .08       0   867.9    .045       0   891.9     .08       0
  985.09     .06       0
#XS Ineff= 2 , 0
          538.71  354.95
Permanent Ineff=
       F       F
Bank Sta=867.9,891.9
XS Rating Curve= 0 ,0
Exp/Cntr=0.3,0.1

Type RM Length L Ch R = 1 ,5147.3  ,179.9,223.3,237
XS GIS Cut Line= 2
     2419067.354      374476.836     2419727.323      373617.738
#Sta/Elev= 30
       0  378.81      36  375.84      88  369.68   111.9   365.8  124.58364.7918
   159.9  360.04   211.9   357.1   275.8  354.77   387.8   352.9   515.7  351.84
   623.6  350.35   727.6  349.41  762.09349.9106   787.5  349.04   807.5  349.12
   827.5  350.13   847.5  351.71   851.5  351.86   855.5  351.16   867.5  348.24
   875.5  347.96   879.5  348.96   883.5  350.85   887.4  352.41  902.29352.9756
  910.11353.1122  935.66353.3265   995.4  355.58  1039.4  358.09  1083.3  361.23
#Mann= 8 ,-1 , 0
       0     .06       0  124.58     .08       0  762.09     .08       0
   855.5    .045       0   883.5     .08       0  902.29     .06       0
  910.11     .12       0  935.66     .06       0
Bank Sta=855.5,883.5
XS Rating Curve= 0 ,0
Exp/Cntr=0.3,0.1

Type RM Length L Ch R = 1 ,4923.9  ,55.4,54.4,53.6
XS GIS Cut Line= 4
     2419154.984      374568.999     2419640.972      373929.643
     2419799.826      373848.914      2419886.28       373748.73
#Sta/Elev= 30
       0  371.05    51.9  365.58  132.08360.3357   167.8  358.04   183.8  356.33
   211.8  354.73   315.6   351.2   387.6  350.75   483.4  351.02   635.3  349.52
  761.95349.0258   783.1  349.82   830.8  348.71   886.2  350.23   894.2   348.8
   902.1  347.41     906  347.74     910  349.12  913.09350.8968  915.72 351.839
   925.8  353.54  945.92354.9088     993  358.11 1021.89359.2546 1022.19359.2608
 1061.44 360.668 1066.51 360.893    1101362.5492 1110.84362.8521  1113.6  362.93
#Mann= 14 ,-1 , 0
       0     .06       0  132.08     .08       0  761.95     .08       0
   894.2    .045       0     910     .08       0  913.09     .12       0
  915.72     .06       0  945.92     .12       0 1021.89     .08       0
 1022.19     .12       0 1061.44     .06       0 1066.51     .12       0
    1101     .08       0 1110.84     .12       0
#XS Ineff= 2 , 0
          455.49   360.8
Permanent Ineff=
       F       F
Bank Sta=894.2,910
XS Rating Curve= 0 ,0
Exp/Cntr=0.3,0.1

Type RM Length L Ch R = 1 ,4869.5  ,209.2,188.1,176.1
XS GIS Cut Line= 4
     2419192.152      374608.089     2419672.222      373976.518
     2419831.076      373891.883     2419924.384       373780.13
#Sta/Elev= 30
       0  368.86    23.9  364.79    51.8   362.1   119.6  358.46  155.42 357.214
   203.3  354.66  309.36351.4892   382.7  350.29  590.53349.4881  747.65349.1385
   801.3  349.38   837.3  348.56   873.3  349.22   877.3  349.04   881.1  348.05
   885.3  347.07   893.3  346.45   897.3   347.6   901.3  351.94  903.31353.2666
   905.3  354.58   909.3  355.57   921.3  355.93  936.46357.5265  942.58358.1516
  991.91359.7882  1024.5  361.09 1038.97361.0416 1048.17361.1318  1118.9  361.56
#Mann= 13 ,-1 , 0
       0     .12       0  155.42     .08       0  309.36     .12       0
  590.53     .08       0  747.65     .08       0   881.1    .045       0
   897.3     .08       0  903.31     .12       0  936.46     .06       0
  942.58     .12       0  991.91     .06       0 1038.97     .12       0
 1048.17     .06       0
#XS Ineff= 2 , 0
          522.07  358.33
Permanent Ineff=
       F       F
Bank Sta=881.1,897.3
XS Rating Curve= 0 ,0
Exp/Cntr=0.3,0.1

Type RM Length L Ch R = 1 ,4681.4  ,527.7,512.8,514
XS GIS Cut Line= 2
     2419350.873      374798.324     2419991.664      373835.574
#Sta/Elev= 30
       0  361.41   139.6  354.26   195.4  352.26  260.78350.5184   330.7348.5413
   366.9  347.66   434.7  347.02  565.43346.9291  782.39346.6441   821.5  346.64
   857.4   348.8   865.4  348.88   869.4  348.63   877.4     347   881.3  346.85
   889.3  345.37   893.3  345.07   897.3  345.47   901.3  347.18   905.3   351.1
   909.2  353.44   913.2  354.21   917.2   354.4  926.03353.9709   937.2  354.03
   969.1  356.07     985  356.63  1048.8  356.55 1141.84355.0605  1156.5  354.99
#Mann= 9 ,-1 , 0
       0     .06       0  260.78     .08       0   330.7     .06       0
  565.43     .08       0  782.39     .08       0   881.3    .045       0
   901.3     .08       0  926.03     .06       0 1141.84     .12       0
#XS Ineff= 2 , 0
          458.51  357.66
Permanent Ineff=
       F       F
Bank Sta=881.3,901.3
XS Rating Curve= 0 ,0
Exp/Cntr=0.3,0.1

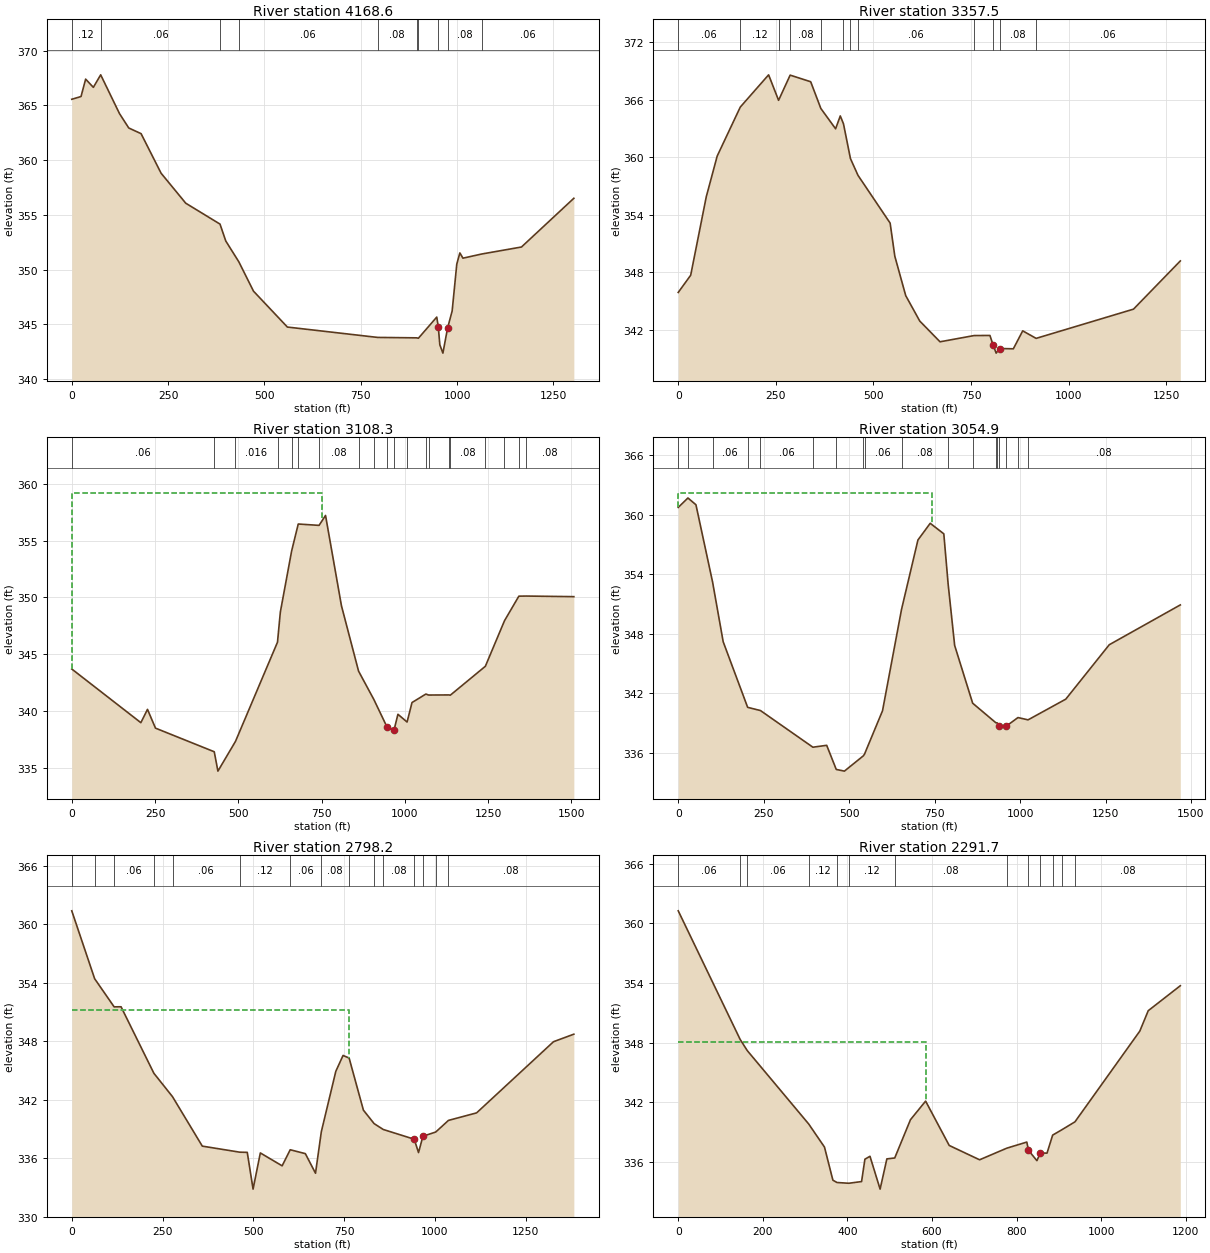
Type RM Length L Ch R = 1 ,4168.6  ,787.7,811.1,727.6
XS GIS Cut Line= 2
     2419486.922      375210.329      2420208.07       374125.13
#Sta/Elev= 30
       0  365.55      24   365.8      36  367.39      56  366.64   75.04367.7829
   123.9  364.24   147.9  362.93   179.9  362.41   231.8   358.8   295.8  356.06
  384.71354.1521   399.7  352.61  433.79350.6949   471.6  348.03   559.6  344.75
  793.93343.8037  894.98343.7652  899.61  343.73   947.2  345.66   951.2  344.78
   955.2  343.13   963.2  342.37   975.2  344.64   987.2  346.22   999.2   350.5
  1007.2  351.52  1015.2  351.04 1063.41351.4169  1167.1  352.06    1303  356.51
#Mann= 10 ,-1 , 0
       0     .12       0   75.04     .06       0  384.71     .08       0
  433.79     .06       0  793.93     .08       0  894.98     .12       0
  899.61     .08       0   951.2    .045       0   975.2     .08       0
 1063.41     .06       0
Bank Sta=951.2,975.2
XS Rating Curve= 0 ,0
Exp/Cntr=0.3,0.1

Type RM Length L Ch R = 1 ,3357.5  ,250.4,249.3,209.2
XS GIS Cut Line= 3
     2419497.017      375514.123       2420067.3      375131.912
     2420372.219      374615.664
#Sta/Elev= 30
       0  345.92    31.9  347.71    71.8  355.88    99.8  360.12  158.94365.2211
   231.5  368.58  257.05 365.926  286.68 368.548   339.3  367.86  365.31365.0776
   403.1  362.96   415.1   364.3   423.3363.4765  441.09359.8635  460.43358.1156
   542.8  353.14   554.8  349.69   582.7  345.59   618.7  342.94   670.6  340.78
  757.77341.4283   798.4  341.44   806.4  340.47   814.4   339.6   823.1  340.08
   858.4  340.05   882.4  341.92  916.78341.1362  1166.2  344.18  1286.1   349.2
#Mann= 12 ,-1 , 0
       0     .06       0  158.94     .12       0  257.05    .016       0
  286.68     .08       0  365.31     .12       0   423.3     .06       0
  441.09     .12       0  460.43     .06       0  757.77     .08       0
   806.4    .045       0   823.1     .08       0  916.78     .06       0
Bank Sta=806.4,823.1
XS Rating Curve= 0 ,0
Exp/Cntr=0.3,0.1

Type RM Length L Ch R = 1 ,3108.3  ,58.5,53.4,85.2
XS GIS Cut Line= 5
      2419660.01      375989.173     2420142.317      375348.379
     2420228.038      375206.235     2420242.795      375158.709
     2420442.516      374711.197
#Sta/Elev= 30
       0  343.71   207.5  338.99   227.4  340.16   251.4  338.51  427.88336.4333
   438.9  334.73  491.66337.3444  617.84346.0678   626.4  348.72   660.3354.0898
  680.15356.4572  742.68356.3376   762.1  357.21   809.9  349.27   861.3  343.52
  907.22341.0283   946.4  338.63     968  338.36   979.5  339.73 1006.97339.0453
  1021.8  340.76  1063.4 341.507 1071.58  341.42 1133.22341.4298  1136.7341.4045
 1242.05343.9476 1299.52347.9518 1342.68350.1145 1364.65350.1231  1507.8  350.07
#Mann= 20 ,-1 , 0
       0     .06       0  427.88     .12       0  491.66    .016       0
  617.84    .016       0   660.3     .08       0  680.15    .016       0
  742.68     .08       0   861.3    .016       0  907.22     .08       0
   946.4    .045       0     968    .016       0 1006.97     .06       0
  1063.4    .016       0 1071.58     .08       0 1133.22    .016       0
  1136.7     .08       0 1242.05    .016       0 1299.52     .08       0
 1342.68    .016       0 1364.65     .08       0
#XS Ineff= 2 , 0
          752.59   359.2
Permanent Ineff=
       F       F
Bank Sta=946.4,968
XS Rating Curve= 0 ,0
Exp/Cntr=0.3,0.1

Type RM Length L Ch R = 1 ,3054.9  ,252.5,256.7,262.9
XS GIS Cut Line= 4
     2419738.757      376020.961     2420205.034      375389.612
     2420374.305      374996.382     2420481.572      374764.273
#Sta/Elev= 30
       0  360.72   28.38361.6708    51.8  360.99  100.46353.2086   131.5  347.19
  203.06340.5849  240.54340.2607  393.91336.5688   434.3  336.76  462.24334.3298
   486.1  334.16  541.68335.7049  544.98 335.877   597.6  340.24  653.13350.4359
   701.2  357.44   737.1  359.12   776.9  358.06  789.39353.0568   808.6  346.82
  861.26341.0023  929.02339.0345  933.13339.0233   937.8  338.72   959.3  338.68
  993.76339.5555 1023.31339.3231  1133.7  341.41  1260.9  346.89  1468.7   350.9
#Mann= 18 ,-1 , 0
       0     .08       0   28.38     .12       0  100.46     .06       0
  203.06    .016       0  240.54     .06       0  393.91     .12       0
  462.24     .06       0  541.68     .08       0  544.98     .06       0
  653.13     .08       0  789.39     .12       0  861.26     .06       0
  929.02    .016       0  933.13     .12       0   937.8    .045       0
   959.3     .12       0  993.76    .016       0 1023.31     .08       0
#XS Ineff= 2 , 0
           742.5  362.19
Permanent Ineff=
       F       F
Bank Sta=937.8,959.3
XS Rating Curve= 0 ,0
Exp/Cntr=0.3,0.1

Type RM Length L Ch R = 1 ,2798.2  ,410.1,506.5,438.6
XS GIS Cut Line= 3
     2419887.559      376081.028     2420123.871      375924.551
     2420699.463      374988.303
#Sta/Elev= 30
       0  361.36      63354.3978  116.65351.5128   135.7  351.52   226.1 344.701
  277.41 342.299   359.4  337.23  462.56336.6089   483.2  336.59   499.2  332.82
   519.2  336.53   579.2  335.21  601.46336.8567   643.1  336.46   671.1  334.45
  687.11338.7014     727   344.9     747  346.53  763.64 346.264     803  340.92
  832.58339.5344  857.66338.9362   942.8  337.94   954.8  336.57   966.8  338.24
 1002.16338.6776 1037.16339.8672  1114.7  340.64  1326.5  347.94  1382.4  348.71
#Mann= 15 ,-1 , 0
       0     .06       0      63     .08       0  116.65     .06       0
   226.1    .016       0  277.41     .06       0  462.56     .12       0
  601.46     .06       0  687.11     .08       0  763.64     .06       0
  832.58     .08       0  857.66     .08       0   942.8    .045       0
   966.8     .08       0 1002.16     .12       0 1037.16     .08       0
#XS Ineff= 2 , 0
          762.67  351.21
Permanent Ineff=
       F       F
Bank Sta=942.8,966.8
XS Rating Curve= 0 ,0
Exp/Cntr=0.3,0.1

Type RM Length L Ch R = 1 ,2291.7  ,382.1,470.9,405.8
XS GIS Cut Line= 4
     2420632.665      376229.724     2420501.475      376012.225
     2420840.017      375348.162      2420978.77      375222.023
#Sta/Elev= 30
       0  361.27  146.33348.3454  163.14347.2203  308.34 339.843   345.7  337.52
   365.6  334.19  375.31333.9557  403.12  333.88   433.4  334.05   441.3   336.3
   453.3  336.59   477.2  333.29   493.2  336.33   511.8336.4215     549  340.27
   584.8  342.14   640.6  337.68   712.4  336.24  777.01337.4118     824  338.02
     828  337.19   847.9  336.15   855.9  336.92   871.8  336.91  885.13338.7197
  906.64339.2535   937.8340.0535  1091.2  349.18  1111.1  351.23  1186.9  353.74
#Mann= 13 ,-1 , 0
       0     .06       0  146.33     .08       0  163.14     .06       0
  308.34     .12       0  375.31     .04       0  403.12     .12       0
   511.8     .08       0  777.01     .08       0     828    .045       0
   855.9     .08       0  885.13     .12       0  906.64     .06       0
   937.8     .08       0
#XS Ineff= 2 , 0
          585.62  348.04
Permanent Ineff=
       F       F
Bank Sta=828,855.9
XS Rating Curve= 0 ,0
Exp/Cntr=0.3,0.1

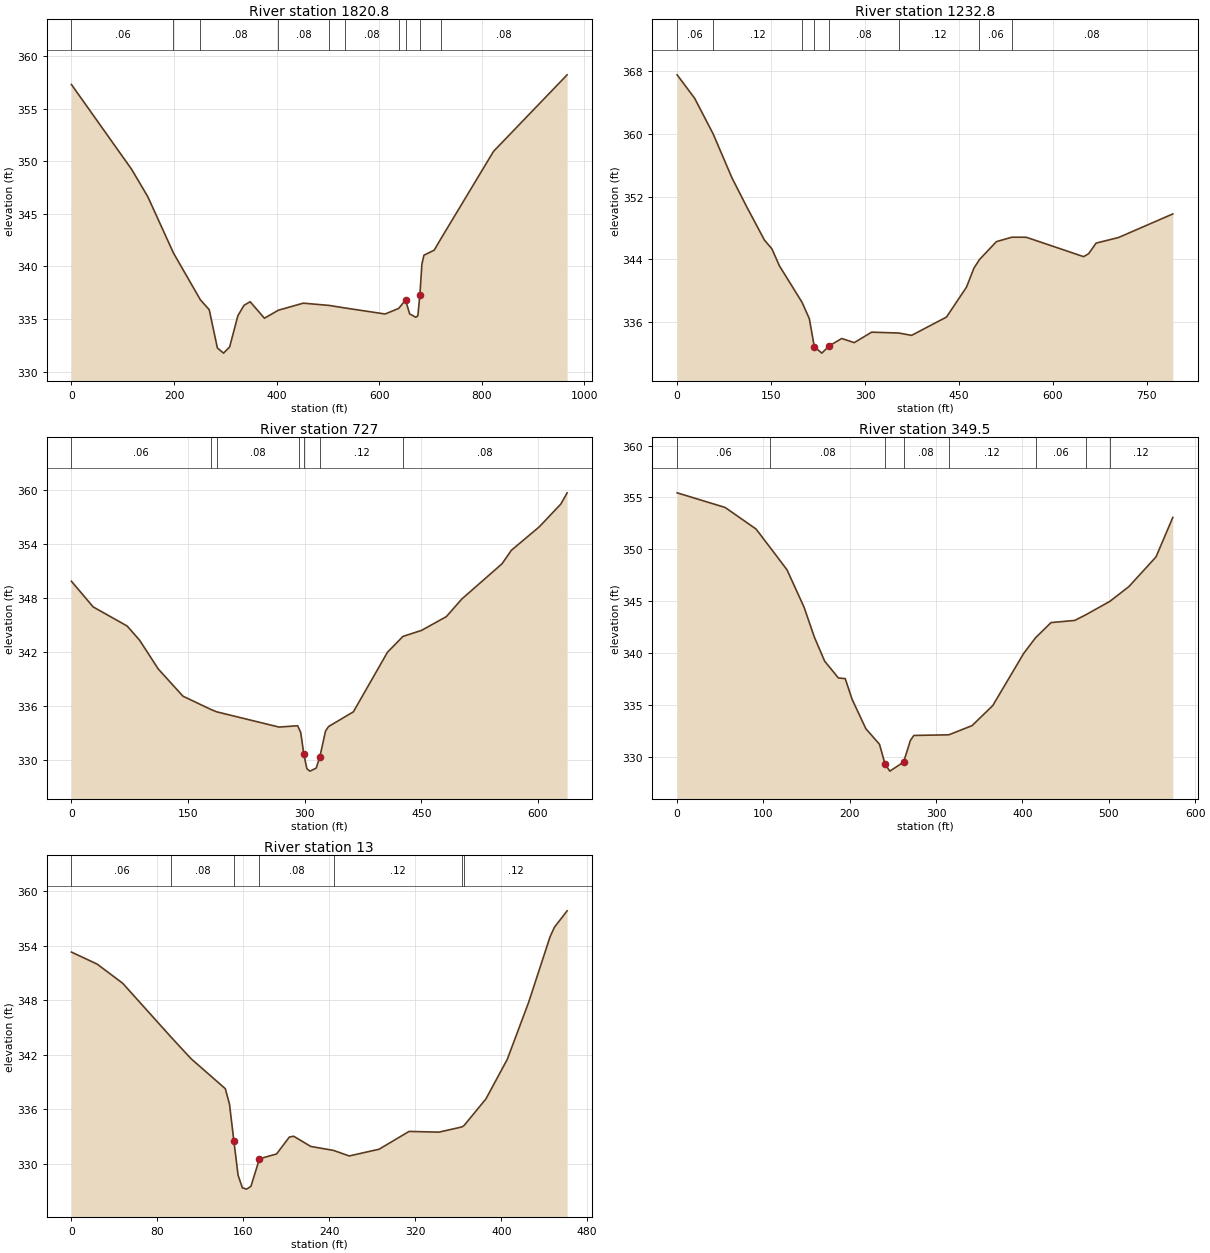
Type RM Length L Ch R = 1 ,1820.8  ,565,587.9,551.6
XS GIS Cut Line= 3
     2420809.128      376247.371     2420787.933      376112.051
     2421226.275      375407.979
#Sta/Elev= 30
       0  357.29   117.4  349.22   148.9  346.62  198.89341.2687  251.46336.8127
   268.6  335.88   284.5  332.24   296.5  331.75   308.4  332.34   324.4   335.3
   336.3  336.29   348.3  336.64   376.2  335.07  403.38335.8312     452   336.5
  502.57336.2846  532.53  336.05   611.5  335.47  637.92335.9978   651.3   336.8
   659.3  335.48   671.3  335.16   675.3   335.3   679.2  337.26   683.2  340.22
   687.2  341.06   707.2  341.54   720.1 342.615   822.8  350.93   966.3  358.21
#Mann= 10 ,-1 , 0
       0     .06       0  198.89     .12       0  251.46     .08       0
  403.38     .08       0  502.57     .12       0  532.53     .08       0
  637.92     .12       0   651.3    .045       0   679.2     .06       0
   720.1     .08       0
Bank Sta=651.3,679.2
XS Rating Curve= 0 ,0
Exp/Cntr=0.3,0.1

Type RM Length L Ch R = 1 ,1232.8  ,504.7,505.8,455.8
XS GIS Cut Line= 3
      2421231.38      376290.502     2421341.606      375590.245
     2421391.036       375524.06
#Sta/Elev= 30
       0  367.56    27.9  364.57   57.39360.0279    87.6  354.38   111.5  350.63
   139.4  346.44   151.3  345.32   163.3  343.15  199.31338.5043   211.1  336.39
     219  332.81     231  331.99   242.9  332.92   262.8  333.86   282.8  333.33
   310.6  334.67  353.84334.5613   374.4  334.26   430.1   336.6     462  340.42
   473.9  342.85  482.78343.9504   509.8  346.24  534.33346.8037   557.5   346.8
   649.1  344.32   657.1   344.7     669  346.05   704.9  346.77   791.5  349.78
#Mann= 8 ,-1 , 0
       0     .06       0   57.39     .12       0  199.31     .08       0
     219    .045       0   242.9     .08       0  353.84     .12       0
  482.78     .06       0  534.33     .08       0
Bank Sta=219,242.9
XS Rating Curve= 0 ,0
Exp/Cntr=0.3,0.1

Type RM Length L Ch R = 1 ,727     ,370.1,377.5,293.5
XS GIS Cut Line= 3
     2421638.985      376333.541     2421706.189      375892.329
      2421715.98      375701.404
#Sta/Elev= 30
       0  349.85    27.9     347    71.7  344.87    87.7  343.29   111.6   340.1
   143.4  337.07  178.95 335.607  186.86335.3265     267  333.63   290.9  333.78
  292.93333.3943   294.9  333.02   298.9   330.6   302.8     329   306.8  328.73
   314.8  329.07   319.5  330.33   326.8  333.19   330.7  333.69   362.6  335.33
   406.4  341.95  426.32343.7136   450.3  344.39   482.2  345.92   502.1  347.88
   553.8   351.8   565.8   353.3   601.6   355.9   629.5  358.45   637.5  359.69
#Mann= 7 ,-1 , 0
       0     .06       0  178.95     .12       0  186.86     .08       0
  292.93     .12       0   298.9    .045       0   319.5     .12       0
  426.32     .08       0
Bank Sta=298.9,319.5
XS Rating Curve= 0 ,0
Exp/Cntr=0.3,0.1

Type RM Length L Ch R = 1 ,349.5   ,335.5,336.6,336.7
XS GIS Cut Line= 3
     2422075.689      376250.075     2421878.733      375859.865
     2421884.903      375722.854
#Sta/Elev= 30
       0  355.45    55.6  354.04    91.4  351.96  107.71  350.18   127.2  348.04
     147  344.43     159  341.53   170.9  339.22   186.8   337.6   194.7  337.54
   202.6  335.56   218.6  332.71   234.4  331.21   240.9  329.28   246.4  328.62
   262.3  329.49   270.2  331.58   274.2  332.06  314.76332.1223   341.7  333.01
   365.6  334.94   401.3  339.95  415.13341.4718   433.1  342.94   460.6  343.15
  473.15343.6808  501.24 344.986   523.3  346.41   554.7  349.27   574.2  353.08
#Mann= 8 ,-1 , 0
       0     .06       0  107.71     .08       0   240.9    .045       0
   262.3     .08       0  314.76     .12       0  415.13     .06       0
  473.15     .08       0  501.24     .12       0
Bank Sta=240.9,262.3
XS Rating Curve= 0 ,0
Exp/Cntr=0.3,0.1

Type RM Length L Ch R = 1 ,13      ,12.2,13,13.7
XS GIS Cut Line= 2
     2422295.935      376066.309      2422048.54      375676.986
#Sta/Elev= 30
       0   353.3    23.9  351.98    47.7  349.87   92.85343.9285   111.3  341.57
   143.2  338.27   147.1  336.56   151.1  332.57   155.1  328.74   159.1  327.36
     163  327.22     167  327.52     175  330.56   190.9  331.09   202.8  332.95
   206.8  333.04   222.7  331.92  243.92331.4789   258.5  330.87   286.3  331.61
   314.2  333.57     342  333.49  363.23334.0589  365.41 334.221   385.7  337.14
   405.6   341.5   425.5  347.78   445.4  354.98   449.4  356.02   461.3  357.84
#Mann= 7 ,-1 , 0
       0     .06       0   92.85     .08       0   151.1    .045       0
     175     .08       0  243.92     .12       0  363.23     .06       0
  365.41     .12       0
Bank Sta=151.1,175
XS Rating Curve= 0 ,0
Exp/Cntr=0.3,0.1

Chan Stop Cuts=-1
Use User Specified Reach Order=0
Composite Channel Slope=5